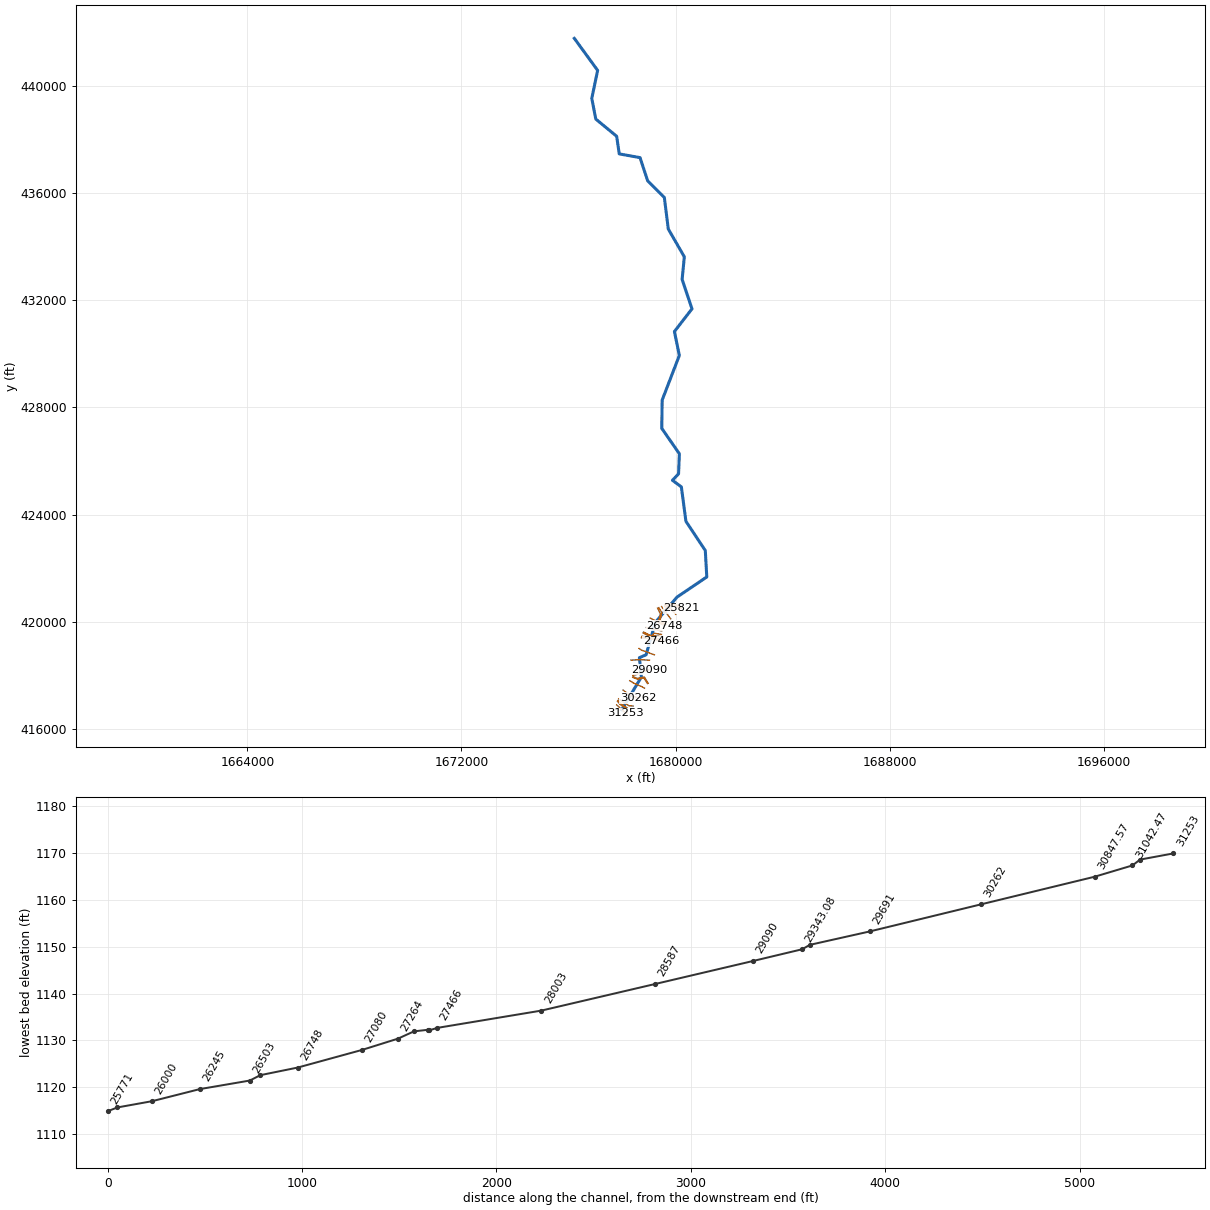
--- SUGARRN.prj (project) ---

Proj Title=SUGARRN
Current Plan=p01
Default Exp/Contr=0,0
English Units
Geom File=g01
Flow File=f01
Plan File=p01
BEGIN DESCRIPTION:
---------- MODELED AS PART OF WVEMD CTP PROGRAM, 2023----------
Stream Name: Sugar Run
Flood Zone:  AFH
Wetzel County, WV
HEC-RAS Version: RAS 6.3
Vertical Datum: NAVD88
Projection: NAD 1983 StatePlane West Virginia S FIPS 4702 (US Feet)
Terrain: 1-meter West Virginia FEMA R3 South Central (collected 2018-2020)
Land Use: 2019 NLCD
Hydrologic Method:
WV SIR2010-5033 regression equations
Additional Model Notes:
None
END DESCRIPTION:
DSS File=dss
DSS Export Rating Curves= 0
DSS Export Rating Curve Sorted= 0
DSS Export Volume Flow Curves= 0
DXF OffsetX= 0
DXF OffsetY= 0
DXF ScaleX= 0
DXF ScaleY= 0

--- SUGARRN.p01 (plan) ---

Plan Title=Floodplain
Program Version=6.30
Short Identifier=Floodplain
Geom File=g01
Flow File=f01
Subcritical Flow
K Sum by GR= 0
Std Step Tol= 0.01
Critical Tol= 0.01
Num of Std Step Trials= 20
Max Error Tol= 0.3
Flow Tol Ratio= 0.001
Split Flow NTrial= 30
Split Flow Tol= 0.02
Split Flow Ratio= 0.02
Log Output Level= 0
Friction Slope Method= 1
Unsteady Friction Slope Method= 2
Unsteady Bridges Friction Slope Method= 1
Parabolic Critical Depth
Global Vel Dist= 0 , 0 , 0
Global Log Level= 0
CheckData=True
Encroach Param=-1 ,0,0, 0
Computation Interval=0.1SEC
Output Interval=1SEC
Instantaneous Interval=Max Profile
Mapping Interval=1HOUR
Computation Time Step Use Courant=        0
Computation Time Step Use Time Series=    0
Computation Time Step Count To Double=0
Computation Time Step Max Doubling=0
Computation Time Step Max Halving=0
Computation Time Step Residence Courant=0
Run HTab= 0
Run UNet= 0
Run Sediment= 0
Run PostProcess= 0
Run WQNet= 0
Run RASMapper= 0
UNET Theta= 0
UNET Theta Warmup= 0
UNET ZTol= 0
UNET ZSATol= 0
UNET MxIter= 0
UNET Max Iter WO Improvement= 0
UNET MaxInSteps= 0
UNET DtIC= 0
UNET DtMin= 0
UNET MaxCRTS= 0
UNET WFStab= 0
UNET SFStab= 0
UNET WFX= 1
UNET SFX= 1
UNET Gravity=32.17405
UNET 1D Methodology=Finite Difference
UNET DSS MLevel= 1
UNET Pardiso=0
UNET DZMax Abort= 0
UNET Use Existing IB Tables= 0
UNET Froude Reduction=False
UNET Froude Limit= 0
UNET Froude Power= 0
UNET D1 Cores= 0
UNET WindReference=Eulerian
UNET WindDragFormulation=Hsu (1988)
UNET D2 Coriolis=0
UNET D2 Cores= 0
UNET D2 Theta= 1
UNET D2 Theta Warmup= 1
UNET D2 Z Tol= 0.01
UNET D2 Volume Tol= 0.01
UNET D2 Max Iterations= 20
UNET D2 Equation= 0
UNET D2 RampUpFraction=0.1
UNET D2 TimeSlices= 1
UNET D2 Turbulence Formulation=Non-Conservative (original)
UNET D2 Eddy Viscosity=0.3
UNET D2 Transverse Eddy Viscosity=0.1
UNET D2 Smagorinsky Mixing=0
UNET D2 BCVolumeCheck=0
UNET D2 Cores=0
UNET D2 SolverType=PARDISO (Direct)
UNET D2 Minimum Iterations= 3
UNET D2 Maximum Iterations= 30
UNET D2 Restart Number= 10
UNET D2 Relaxation Coeff=1.3
UNET D2 SOR Precondition Iterations= 10
UNET D2 ILUT Maximum Fill= 8
UNET D2 ILUT Tolerance=1E-08
UNET D2 Convergence Tolerance=0.00001
UNET D1D2 MaxIter= 0
UNET D1D2 ZTol=0.01
UNET D1D2 QTol=0.1
UNET D1D2 MinQTol=1
DSS File=dss
Write IC File= 0
Write IC File at Fixed DateTime=0
Write IC File at Sim End=0
Echo Input=False
Echo Parameters=False
Echo Output=False
Write Detailed= 0
HDF Write Warmup=0
HDF Write Time Slices=0
HDF Flush=0
HDF Compression= 1
HDF Chunk Size= 1
HDF Spatial Parts= 1
HDF Use Max Rows=0
HDF Fixed Rows= 1
Calibration Method= 0
Calibration Iterations= 20
Calibration Max Change=0.05
Calibration Tolerance=0.2
Calibration Maximum=1.5
Calibration Minimum=0.5
Calibration Optimization Method= 1
WQ AD Non Conservative
WQ ULTIMATE=-1
WQ Max Comp Step=1HOUR
WQ Output Interval=15MIN
WQ Output Selected Increments= 0
WQ Output face flow=0
WQ Output face velocity=0
WQ Output face area=0
WQ Output face dispersion=0
WQ Output cell volume=0
WQ Output cell surface area=0
WQ Output cell continuity=0
WQ Output cumulative cell continuity=0
WQ Output face conc=0
WQ Output face dconc_dx=0
WQ Output face courant=0
WQ Output face peclet=0
WQ Output face adv mass=0
WQ Output face disp mass=0
WQ Output cell mass=0
WQ Output cell source sink temp=0
WQ Output nsm pathways=0
WQ Output nsm derived pathways=0
WQ Create Restart=0
WQ Fixed Restart=0
WQ System Summary=0
WQ Write To DSS=0
Sorting and Armoring Iterations= 10
XS Update Threshold= 0.02
Bed Roughness Predictor= 0
Hydraulics Update Threshold= 0.02
Energy Slope Method= 1
Volume Change Method= 1
Sediment Retention Method= 0
Sediment TS Multiplier= 1
Warm Up Method= 0
XS Weighting Method= 0
Number of US Weighted Cross Sections= 1
Number of DS Weighted Cross Sections= 1
Upstream XS Weight=0
Main XS Weight=1
Downstream XS Weight=0
Number of DS XS's Weighted with US Boundary= 1
Upstream Boundary Weight= 1
Weight of XSs Associated with US Boundary= 0
Number of US XS's Weighted with DS Boundary= 1
Downstream Boundary Weight= 0.5
Weight of XSs Associated with DS Boundary= 0.5
Percentile Method= 0
Sediment Output Level= 3
Mass or Volume Output= 0
Output Increment Type= 1
Profile and TS Output Increment= 1
Transport Output Increment 1
XS Output Flag= 0
XS Output Increment= 10
Read HDF5 Sediment Hotstart= 0
Sediment Hotstart Type= 0
Write Gradation File= 0
Read Gradation Hotstart= 0
Write HDF5 File= 1
Write Binary Output= 1
Write DSS Sediment File= 0
DSS Sediment Output Type= 1
SV Curve= 0
Specific Gage Flag= 0
Subcell Erosion Methods= 0
Subcell Deposition Methods= 0
Advection Scheme= 1
Matrix Solver= 0
Implicit Weighting Factor= 1
Maximum Outer Loop Convergence Iterations= 5
Convergence Maximum Absolute= 0.001
Convergence RMSE= 0.0001
Grain Fractions Max Abs Error= 0.001
Max Subgrid Regions= 1
Max Subgrid Length Scale= 3.402823E+38
Initial Layer Thickness= 3.402823E+38
Min Layer Thickness= 3.402823E+38
Max Layer Thickness= 3.402823E+38
Number of Layers= 5

--- SUGARRN.f01 (steady flow) ---

Flow Title=Flow
Program Version=4.00
Number of Profiles=1
Profile Names=F01pct
River Rch & RM=SUGARRN,Main,31253
     374
River Rch & RM=SUGARRN,Main,29090
     562
River Rch & RM=SUGARRN,Main,27466
     680
River Rch & RM=SUGARRN,Main,25771
     779
River Rch & RM=SUGARRN,Main,24080
     998
River Rch & RM=SUGARRN,Main,22002
    1110
River Rch & RM=SUGARRN,Main,19784
    1240
River Rch & RM=SUGARRN,Main,17000
    1430
River Rch & RM=SUGARRN,Main,14001
    1610
River Rch & RM=SUGARRN,Main,11374
    1800
River Rch & RM=SUGARRN,Main,4002
    2000
Boundary for River Rch & Prof#=SUGARRN,Main      ,1
Up Type=0
Dn Type=3
Dn Slope=0.008623

--- SUGARRN.g01 (geometry) ---

Geom Title=Geometry
Program Version=6.31

River Reach=SUGARRN         ,Main
Reach XY= 30
1677985.83131577416719.0070186911678724.79418873417940.005157558
1678649.18127404418660.554070737 1678901.1725511418771.928114105
1679248.26871098419984.0997630081680056.74971098420921.368763008
1681168.01571098421673.0767630081681112.29471098422659.232763008
1680388.44671098423748.4207630081680218.12971098425032.631763008
1679884.32971098425278.1197630081680112.99571098425517.299763008
1680144.53671098426266.3787630081679485.34671098427215.212763008
1679501.11671098428269.7067630081680142.43371098429933.976763008
1679958.44871098430826.0387630081680615.01071098431672.892763008
1680246.51571098432771.0167630081680328.52071098433613.139763008
1679729.78271098434650.2857630081679582.06971098435827.260763008
1678960.20171098436443.8707630081678674.23771098437312.277763008
1677896.77271098437452.1057630081677800.57471098438108.141763008
1677020.48071098438750.5107630081676870.66471098439521.667763008
1677089.34371098440566.1737630081676217.38971098441761.589763008

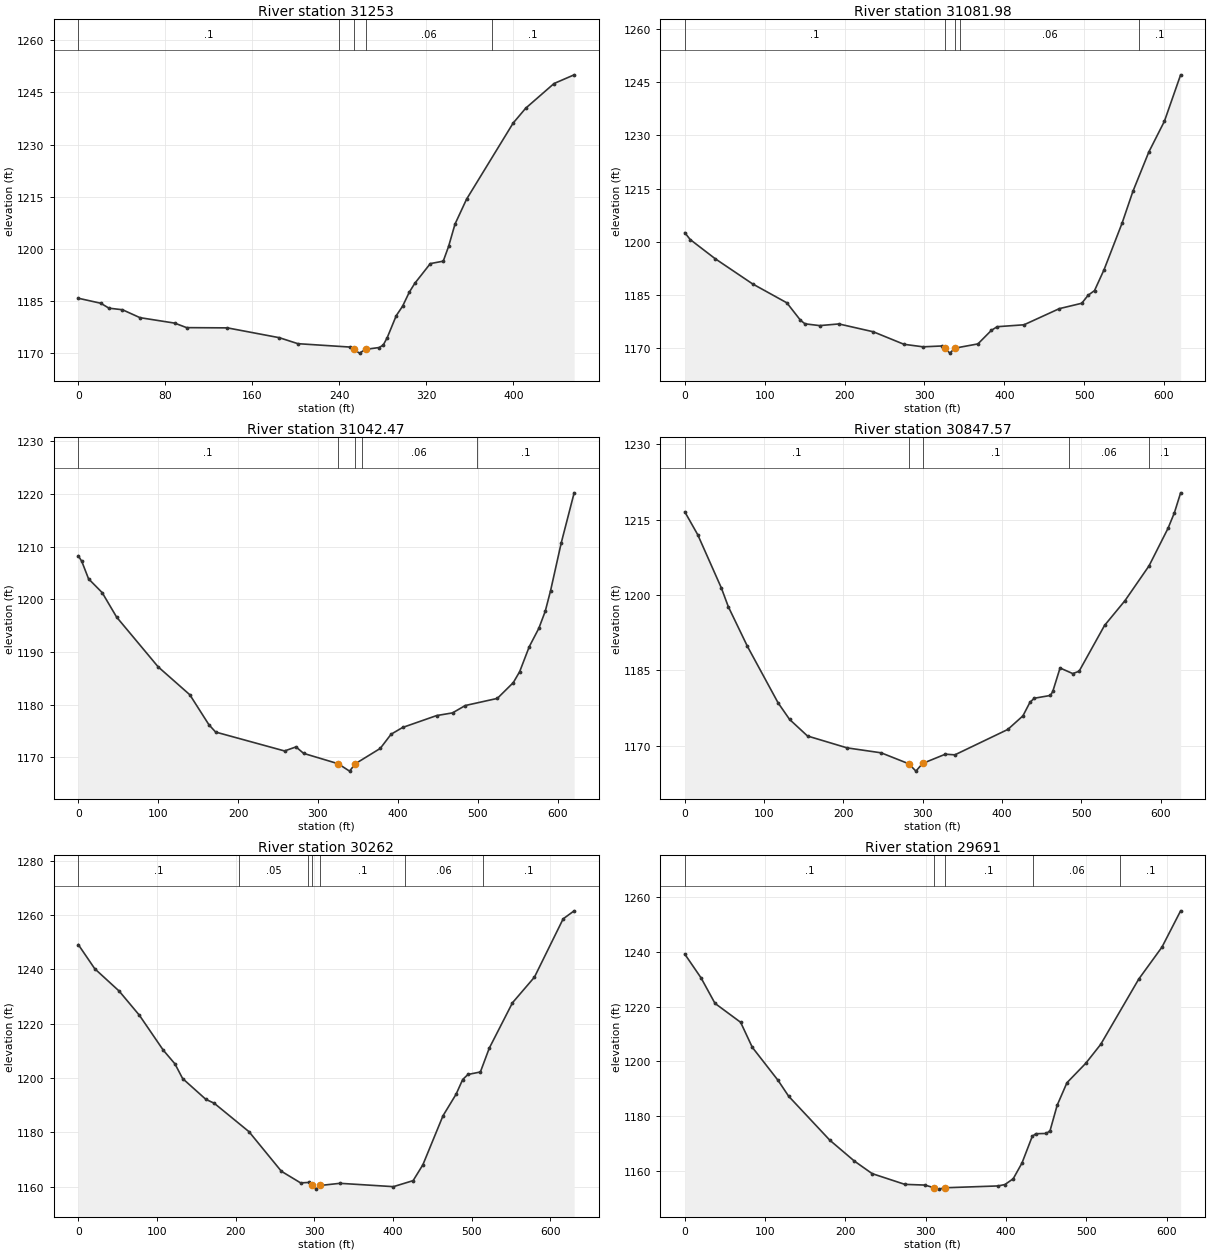
Type RM Length L Ch R = 1 ,31253   ,167.6,171.5,167.4
BEGIN DESCRIPTION:
Structure 15 XS 4
END DESCRIPTION:
XS GIS Cut Line= 2
1677801.85844158416899.354773482 1678141.9343154416595.571581845
#Sta/Elev= 30
       0 1185.75    20.6 1184.31    28.2 1182.89    40.6 1182.44    56.7 1180.16
    88.6 1178.59    99.6 1177.29   137.1 1177.22   184.9 1174.39   201.9 1172.67
   249.7  1171.7  253.111171.046   258.6 1169.95   264.2 1171.04   276.6 1171.56
   280.4 1172.27   284.1 1174.42   292.4 1180.75   298.2 1183.45   304.4 1187.51
   309.5 1190.07   323.7 1195.72   335.6 1196.43   340.5 1200.65   346.4 1207.08
     357 1214.24   399.9 1236.19   411.5 1240.48   437.5 1247.57     456 1250.07
#Mann= 5, -1 ,  0
       0     0.1       0     240    0.06       0  253.11   0.045       0
   264.2    0.06       0     380     0.1       0
Bank Sta=253.11,264.2
XS Rating Curve= 0 ,0
Exp/Cntr(USF)=0,0
Exp/Cntr=0.3,0.1

Type RM Length L Ch R = 1 ,31081.98,38.3,39.5,39.4
BEGIN DESCRIPTION:
Structure 15 XS 3
END DESCRIPTION:
XS GIS Cut Line= 4
1677829.41399657417037.8046351581677928.21074252 416918.84528799
1678173.52239064416756.8723915641678166.80152357 416584.81819453
#Sta/Elev= 30
       0 1202.59     6.8 1200.65      38 1195.26    84.8 1188.16   127.8 1182.81
   144.8 1177.91   150.5 1176.89   168.9 1176.39   192.9 1176.86     236 1174.65
   274.4 1171.12   298.3 1170.41   322.3 1170.65   325.8 1170.02   331.9 1168.63
   338.1 1170.03     367 1171.23   383.9 1175.06   391.1 1176.08   424.7 1176.62
   468.9 1181.17     497 1182.69     505 1184.95     513 1186.27     525 1192.19
   547.5 1205.28     561 1214.21     581 1225.35   600.5 1234.01   620.8  1247.1
#Mann= 5, -1 ,  0
       0     0.1       0   325.8   0.045       0   338.1     0.1       0
  344.64    0.06       0   568.6     0.1       0
Bank Sta=325.8,338.1
XS Rating Curve= 0 ,0
Exp/Cntr(USF)=0,0
Exp/Cntr=0.3,0.1

Type RM Length L Ch R = 1 ,31042.47,181.1,194.9,185.2
BEGIN DESCRIPTION:
Structure 15 XS 2
END DESCRIPTION:
XS GIS Cut Line= 4
 1677850.9207712417069.3927103951677949.71751715416950.433363227
1678195.02916527  416788.4604668 1678188.3082982416616.406269767
#Sta/Elev= 30
       0 1208.27     4.3 1207.22    12.8  1203.9    29.9 1201.27    47.9 1196.64
    99.9 1187.19   139.6 1181.88   163.5 1176.19   171.9  1174.8   258.2 1171.21
   272.5 1171.98   282.1 1170.75   325.2 1168.79   339.6 1167.38   346.8 1168.78
     378 1171.69   391.6 1174.39     406 1175.67   448.6 1177.93   468.5 1178.44
   484.5 1179.84   524.6 1181.19   544.6 1184.19   552.6 1186.28   564.6 1191.02
   576.6 1194.51   584.6 1197.74   591.3 1201.67   604.6 1210.71   620.8 1220.23
#Mann= 5, -1 ,  0
       0     0.1       0   325.2   0.045       0   346.8     0.1       0
  354.64    0.06       0   498.6     0.1       0
Bank Sta=325.2,346.8
XS Rating Curve= 0 ,0
Exp/Cntr(USF)=0,0
Exp/Cntr=0.3,0.1

Type RM Length L Ch R = 1 ,30847.57,568.1,585.4,570.9
BEGIN DESCRIPTION:
Structure 15 XS 1
END DESCRIPTION:
XS GIS Cut Line= 3
1677874.63037281417127.1053384961678259.74586017416867.007028223
1678419.89613233416858.692749679
#Sta/Elev= 30
       0 1216.55    16.3    1212    46.1  1201.4    54.9 1197.66      79 1189.77
   117.6 1178.55   132.1 1175.25   154.7 1171.95   204.5 1169.59   247.6  1168.6
   282.4 1166.42   291.4 1164.96   299.7 1166.48   328.5 1168.33   340.5  1168.2
   407.2 1173.25   426.3 1175.96   435.1 1178.64   440.5 1179.46     461 1180.02
   463.9 1180.81   473.1 1185.48   489.1 1184.37   497.1 1184.83   529.2 1193.95
     555 1198.89   585.3 1205.81   609.3  1213.3   617.3 1216.39   625.1 1220.33
#Mann= 5, -1 ,  0
       0     0.1       0   282.4   0.045       0   299.7     0.1       0
  484.72    0.06       0  584.72     0.1       0
Bank Sta=282.4,299.7
XS Rating Curve= 0 ,0
Exp/Cntr(USF)=0,0
Exp/Cntr=0.3,0.1

Type RM Length L Ch R = 1 ,30262   ,556,571.3,554.5
XS GIS Cut Line= 6
1678039.90658326417454.3235258461678186.43647392417342.189891845
1678255.79165018417307.3438329251678337.84726034417245.961081669
1678500.15172575417194.2594134211678589.13448742417160.354625583
#Sta/Elev= 30
       0  1249.1    20.9 1240.21    51.9 1231.99    77.7 1223.06     108 1210.22
   122.8 1205.19   132.6 1199.77   162.1 1192.12   172.7 1190.69   216.9 1180.22
   258.1 1165.63   282.6 1161.34   292.6 1161.51  296.671160.393   302.6 1159.05
   307.6  1160.4   332.6 1161.19   400.5 1159.96   425.6 1162.18     438 1168.03
   463.6 1186.09   480.2    1194   488.6 1199.42   495.3 1201.28   511.1  1202.2
   522.4 1210.98   551.9 1227.69   579.8 1237.12   616.3 1258.59   630.3 1261.55
#Mann= 7, -1 ,  0
       0     0.1       0  204.61    0.05       0  292.22     0.1       0
  296.67   0.045       0   307.6     0.1       0   414.7    0.06       0
  514.91     0.1       0
Bank Sta=296.67,307.6
XS Rating Curve= 0 ,0
Exp/Cntr(USF)=0,0
Exp/Cntr=0.3,0.1

Type RM Length L Ch R = 1 ,29691   ,291.6,307.4,297.3
BEGIN DESCRIPTION:
Structure 14 XS 4
END DESCRIPTION:
XS GIS Cut Line= 6
1678289.99842969417802.2503366711678446.07981045417707.869619915
 1678605.5135467417635.6988325071678676.49207928417610.135891507
1678756.63233895417571.516874248 1678840.5524467417526.311256001
#Sta/Elev= 30
       0 1239.16    20.2  1230.5    37.6 1221.16    69.5 1214.25      84 1205.12
   116.1 1193.02   129.3 1187.22   180.5 1171.16   211.1 1163.52   233.2 1158.94
   273.9 1155.01     299 1154.75   310.3 1153.76   316.3 1153.27   323.61153.764
   390.1 1154.44   398.5 1154.95   408.8 1157.06   419.7  1162.8   432.5 1172.55
   436.9 1173.52   450.2 1173.62   454.7 1174.67   463.5 1183.91   475.7 1192.16
   499.1 1199.26   517.7 1206.17     565 1230.01     594 1241.74   617.2 1254.99
#Mann= 5, -1 ,  0
       0     0.1       0   310.3   0.045       0   323.6     0.1       0
  432.89    0.06       0  541.85     0.1       0
Bank Sta=310.3,323.6
XS Rating Curve= 0 ,0
Exp/Cntr(USF)=0,0
Exp/Cntr=0.3,0.1

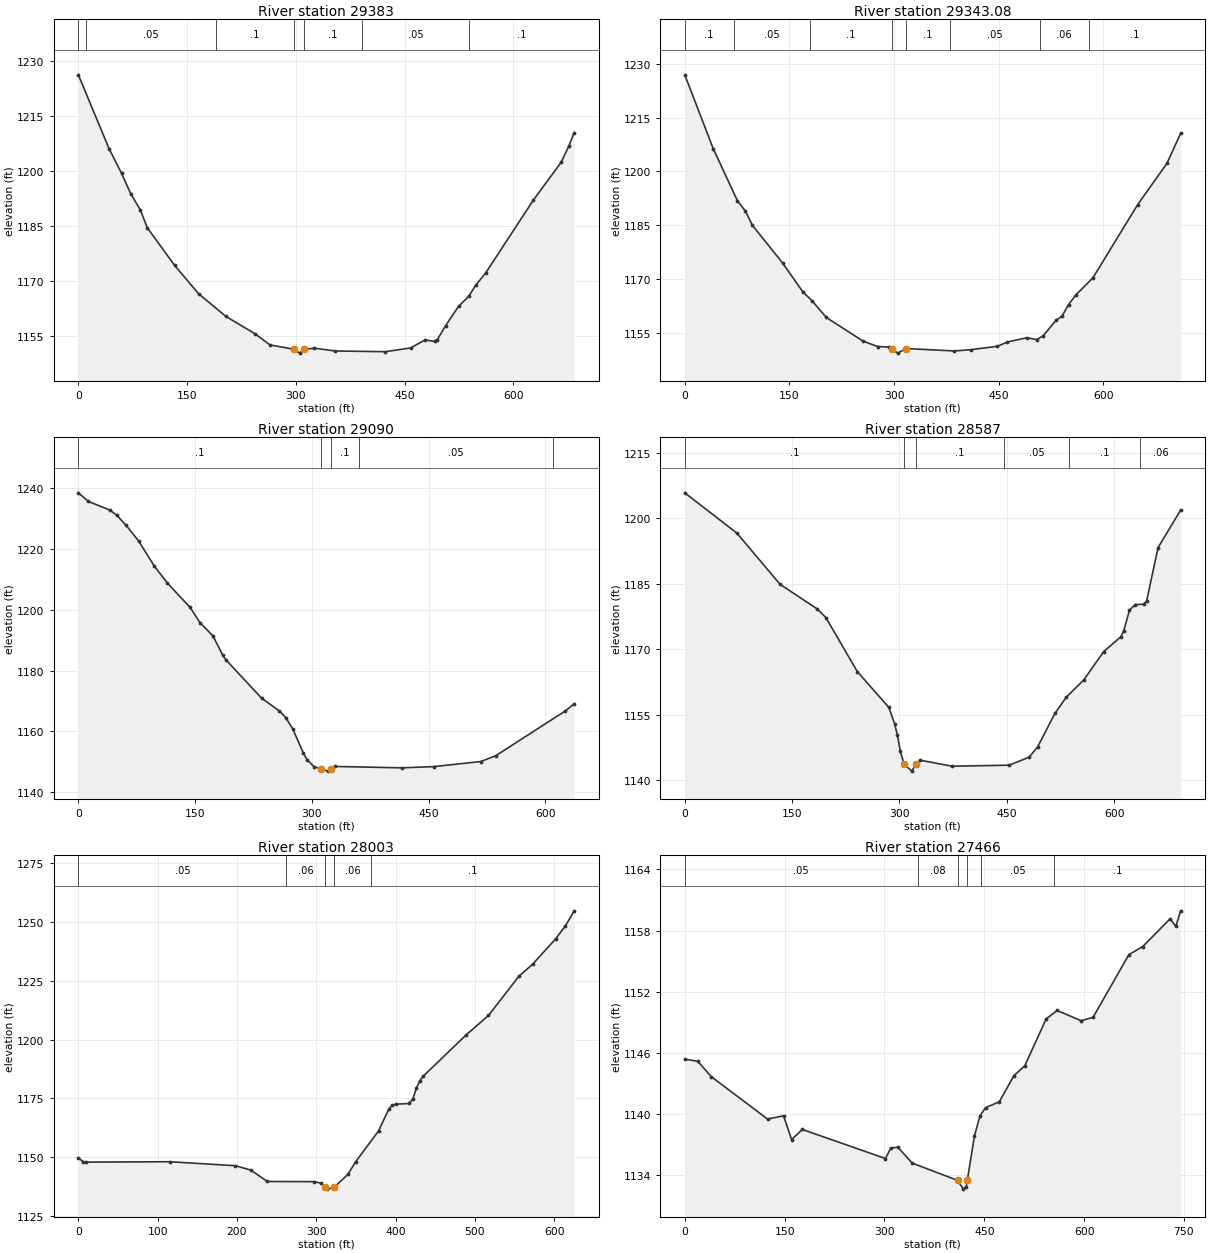
Type RM Length L Ch R = 1 ,29383   ,40.9,40.4,44.8
BEGIN DESCRIPTION:
Structure 14 XS 3
END DESCRIPTION:
XS GIS Cut Line= 6
1678400.80361805417928.8196523841678589.73465907 417853.39658858
1678665.15772287417876.5462418261678703.98939928417880.280056866
1678818.99090251417904.9232361291678950.42119191417698.069882924
#Sta/Elev= 30
       0 1226.27    42.3 1206.18    59.6 1199.44    72.5 1193.76    85.4 1189.51
    95.1  1184.6   132.8 1174.34   165.9 1166.59   203.4 1160.44   243.6  1155.7
   264.5 1152.64   297.4 1151.46   305.4 1150.41  311.561151.435   325.6 1151.76
   354.2    1151   423.7  1150.8   458.4 1151.83   478.3    1154   491.5 1153.62
   495.1 1154.02   506.7 1157.92   524.7  1163.2   538.6 1165.92   548.4 1168.98
   561.8 1172.22   627.5 1192.06   666.1 1202.45   676.4 1206.74     684 1210.51
#Mann= 7, -1 ,  0
       0     0.1       0      10    0.05       0     190     0.1       0
   297.4   0.045       0  311.56     0.1       0  391.34    0.05       0
  538.95     0.1       0
Bank Sta=297.4,311.56
XS Rating Curve= 0 ,0
Exp/Cntr(USF)=0,0
Exp/Cntr=0.3,0.1

Type RM Length L Ch R = 1 ,29343.08,239.4,253,237
BEGIN DESCRIPTION:
Structure 14 XS 2
END DESCRIPTION:
XS GIS Cut Line= 6
1678414.24535219 417951.969305631678571.06558387417888.494449954
1678688.30737612417913.8843922241678739.08726066417921.352022304
1678835.41968868417940.7678605111678975.81113418417707.777802028
#Sta/Elev= 30
       0 1226.88    40.9 1206.27    75.4 1191.88      87 1188.94      97    1185
   140.1 1174.56   169.4 1166.47   182.5 1164.03   202.9 1159.38     256 1152.76
   276.6  1151.3     293 1151.14   297.1 1150.68   305.1 1149.46   317.3 1150.74
   386.6 1150.06   410.8 1150.43   448.3 1151.37   462.5 1152.55   490.5 1153.75
   504.5 1153.22   513.8 1154.28   532.5 1158.64   540.9 1159.73   550.2 1162.98
   560.5  1165.6   585.2 1170.43   649.3 1190.76   691.3 1202.26   710.9 1210.58
#Mann= 8, -1 ,  0
       0     0.1       0      70    0.05       0  179.18     0.1       0
   297.1   0.045       0   317.3     0.1       0  380.49    0.05       0
  508.83    0.06       0  578.83     0.1       0
Bank Sta=297.1,317.3
XS Rating Curve= 0 ,0
Exp/Cntr(USF)=0,0
Exp/Cntr=0.3,0.1

Type RM Length L Ch R = 1 ,29090   ,502.8,503,497.3
BEGIN DESCRIPTION:
Structure 14 XS 1
END DESCRIPTION:
XS GIS Cut Line= 6
1678399.27069393418009.4989246731678494.79314068418020.597327679
1678579.14205334418046.8449785861678739.09711401 418126.77362451
 1678816.6697935418154.8260618451678999.65663226418209.699967846
#Sta/Elev= 30
       0 1238.42    12.9 1235.59    41.1 1232.68    49.2 1231.07    61.3 1227.75
    77.4 1222.61    97.5 1214.38   114.3 1208.79   143.6 1200.75   156.2 1195.79
     173 1191.36   185.6 1184.99   190.1 1183.39   235.5  1170.9   258.2 1166.76
   266.4 1164.57   275.4 1160.84   289.2  1152.8   293.6 1150.77   302.5 1148.46
   311.5 1147.71   320.2 1146.95  323.921147.739   329.1 1148.49   415.4 1148.03
   456.4 1148.43   517.1 1150.11   536.3 1152.04   624.9 1166.62   636.9 1169.07
#Mann= 5, -1 ,  0
       0     0.1       0   311.5   0.045       0  323.92     0.1       0
  359.97    0.05       0  609.15    0.06       0
Bank Sta=311.5,323.92
XS Rating Curve= 0 ,0
Exp/Cntr(USF)=0,0
Exp/Cntr=0.3,0.1

Type RM Length L Ch R = 1 ,28587   ,576.5,584.6,564.1
XS GIS Cut Line= 6
 1678335.1195755418571.5588241671678428.81787892418574.672663093
1678516.26980376418577.5778409991678591.22831526418580.068321586
1678691.17299725 418583.389837251679027.59154793418569.959811973
#Sta/Elev= 30
       0 1205.79      73 1196.53   133.1 1184.84   185.1 1179.18   197.1 1177.23
   241.1 1164.84   285.2 1156.63   293.2  1152.9   297.2 1150.24   301.2 1146.61
   306.4 1143.62   317.2 1142.04   322.9 1143.63   329.2 1144.53   373.2 1143.17
   453.3  1143.4   481.3 1145.24   493.3 1147.66   517.3 1155.29   533.3 1159.02
   557.4 1162.89   585.4 1169.43   609.4 1172.82   613.4 1174.19   621.4  1178.9
   629.4 1180.19   641.4 1180.26   645.4 1181.03   661.4 1193.26   692.9 1201.83
#Mann= 6, -1 ,  0
       0     0.1       0   306.4   0.045       0   322.9     0.1       0
  446.25    0.05       0  536.25     0.1       0  636.25    0.06       0
Bank Sta=306.4,322.9
XS Rating Curve= 0 ,0
Exp/Cntr(USF)=0,0
Exp/Cntr=0.3,0.1

Type RM Length L Ch R = 1 ,28003   ,533.8,536.2,535.3
BEGIN DESCRIPTION:
Structure 13 XS 4
END DESCRIPTION:
XS GIS Cut Line= 6
1678635.21707243419005.436893418  1678719.045973418948.391403839
1678803.65374343418915.1460635071678877.45838584418896.515851423
1679120.95428993418798.1682790821679210.25463626418768.763482258
#Sta/Elev= 30
       0 1149.67     5.9 1148.05     9.9 1147.86   115.4 1148.02   198.1 1146.32
   217.5 1144.46   238.2 1139.61     297 1139.54   305.5 1138.95   310.7 1137.16
   314.1 1136.36   322.7 1137.21   339.8 1142.61   349.5 1147.94   378.5 1161.14
   391.5 1170.46   395.8 1172.03   400.1  1172.5   417.5 1172.81   421.8 1174.87
   426.1 1179.19   430.5 1182.49   434.8 1184.41   489.3 1202.11   517.1 1210.25
   555.4 1226.94   572.9 1232.13   601.8 1242.88   614.1  1248.4   625.1 1254.79
#Mann= 5, -1 ,  0
       0    0.05       0   262.3    0.06       0   310.7   0.045       0
   322.7    0.06       0  368.42     0.1       0
Bank Sta=310.7,322.7
XS Rating Curve= 0 ,0
Exp/Cntr(USF)=0,0
Exp/Cntr=0.3,0.1

Type RM Length L Ch R = 1 ,27466   ,40.9,41.9,42.4
BEGIN DESCRIPTION:
Structure 13 XS 3
END DESCRIPTION:
XS GIS Cut Line= 3
1678724.73545201419405.2418619731679127.31139457419357.096647468
1679455.10859971419267.976782321
#Sta/Elev= 30
       0  1145.4    19.5 1145.19    39.7 1143.69   124.3 1139.53   148.4 1139.85
   160.5 1137.52   176.6 1138.51   301.5 1135.66   309.6 1136.69   320.3 1136.76
   341.8 1135.21   409.8 1133.52   418.7 1132.66   422.9 1132.91  424.711133.583
   435.3 1137.87   443.6 1139.85   451.9 1140.64   472.6 1141.22   494.6 1143.78
   510.8 1144.74   543.1 1149.35   559.5 1150.17   595.6 1149.17   613.5  1149.5
   667.4 1155.65   688.2 1156.44   729.2 1159.15   737.9 1158.42   745.1 1159.94
#Mann= 6, -1 ,  0
       0    0.05       0     350    0.08       0   409.8   0.045       0
  424.71    0.08       0  445.44    0.05       0  555.44     0.1       0
Bank Sta=409.8,424.71
XS Rating Curve= 0 ,0
Exp/Cntr(USF)=0,0
Exp/Cntr=0.3,0.1

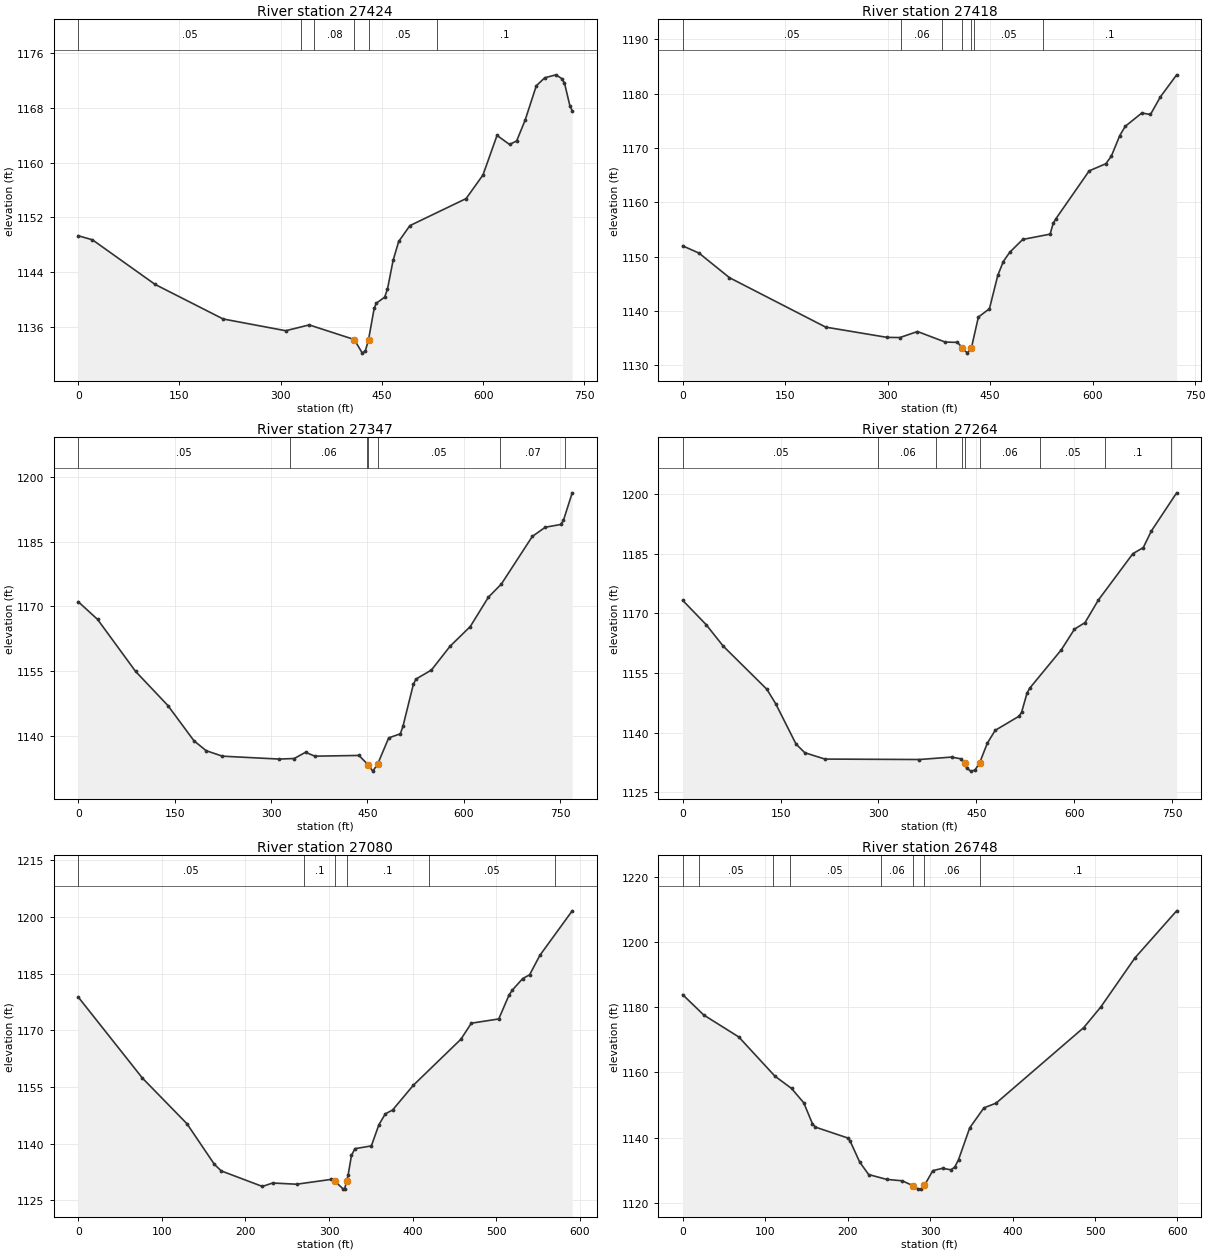
Type RM Length L Ch R = 1 ,27424   ,9.2,6.7,7.3
BEGIN DESCRIPTION:
Structure 13 XS 2
END DESCRIPTION:
XS GIS Cut Line= 4
 1678743.1740448419446.2165126151679137.55505723419396.022565578
 1679199.0170332419379.6327053211679459.20606478419304.853967899
#Sta/Elev= 30
       0 1149.31    21.1 1148.71   113.9 1142.18   214.7 1137.12   307.4  1135.4
   342.2 1136.25     409 1134.11   420.9 1132.12   425.4 1132.46   430.1 1134.08
   438.5 1138.69   441.6 1139.43     454 1140.31   458.2 1141.51   466.5 1145.69
   474.8 1148.47   491.4 1150.79   574.7 1154.75   599.7 1158.21   620.5    1164
   639.1 1162.67   649.6  1163.2   662.1 1166.22   678.7 1171.27   691.2 1172.44
   707.9 1172.87   716.2 1172.33   720.4 1171.69   728.7 1168.24   731.9 1167.63
#Mann= 6, -1 ,  0
       0    0.05       0     330    0.06       0     350    0.08       0
     409   0.045       0   430.1    0.05       0  531.17     0.1       0
Bank Sta=409,430.1
XS Rating Curve= 0 ,0
Exp/Cntr(USF)=0,0
Exp/Cntr=0.3,0.1

Type RM Length L Ch R = 1 ,27418   ,64.8,71,74.8
BEGIN DESCRIPTION:
Structure 12 XS 4 AND Structure 13 XS 1
END DESCRIPTION:
XS GIS Cut Line= 3
1678752.39334119419459.533274074 1679144.7256211419399.095664376
1679466.37662864419345.828618541
#Sta/Elev= 30
       0    1152      24 1150.66    68.5 1146.14   209.3 1137.04   299.2 1135.15
     318 1135.12   343.7 1136.23   384.2 1134.29   402.1 1134.23   409.1 1133.28
   416.6 1132.25  422.731133.284   432.8 1138.89     449 1140.42   461.2 1146.56
   469.3 1149.12   478.7 1150.82   497.7 1153.18   537.8 1154.16   542.3 1156.14
   546.4 1157.02     595 1165.81   619.3 1167.12   627.4 1168.51   639.6 1172.27
   647.7    1174     672 1176.46   684.7 1176.19   699.2 1179.43     723 1183.49
#Mann= 7, -1 ,  0
       0    0.05       0     320    0.06       0     380    0.08       0
   409.1   0.045       0  422.73    0.08       0  426.96    0.05       0
  526.96     0.1       0
Bank Sta=409.1,422.73
XS Rating Curve= 0 ,0
Exp/Cntr(USF)=0,0
Exp/Cntr=0.3,0.1

Type RM Length L Ch R = 1 ,27347   ,78.3,82.4,88.4
BEGIN DESCRIPTION:
Structure 12 XS 3
END DESCRIPTION:
XS GIS Cut Line= 5
1678786.19742798419587.5790573321679111.94590058419406.266228239
1679158.04238255419454.4114427441679197.99266693419480.020599395
1679477.64465757419447.240878881
#Sta/Elev= 30
       0  1171.1    30.1 1167.01    89.2 1154.99   139.5 1147.09   180.1 1138.93
     199 1136.65   224.2 1135.38   312.4 1134.71     336 1134.84   353.6 1136.28
   368.1 1135.38   436.7 1135.55   450.8 1133.42   458.2 1131.92   465.6 1133.47
     483 1139.61   501.1 1140.55   505.2  1142.3   521.3 1151.96   525.3  1153.2
   549.5 1155.31   578.5 1160.81   609.9 1165.36   638.1 1172.15   658.2 1175.18
   706.5 1186.22   726.7 1188.34   750.8 1188.97   754.9 1189.95   768.5 1196.29
#Mann= 7, -1 ,  0
       0    0.05       0     330    0.06       0  449.46    0.05       0
   450.8   0.045       0   465.6    0.05       0  656.92    0.07       0
  756.92     0.1       0
Bank Sta=450.8,465.6
XS Rating Curve= 0 ,0
Exp/Cntr(USF)=0,0
Exp/Cntr=0.3,0.1

Type RM Length L Ch R = 1 ,27264   ,195.2,184.9,173.1
BEGIN DESCRIPTION:
Structure 12 XS 2
END DESCRIPTION:
XS GIS Cut Line= 6
1678804.63602076419617.2856790471679104.77533672419467.728204203
1679128.33576084419491.2886283221679154.96928376419519.970883772
 1679199.0170332419574.2622958731679474.57155877419530.214546432
#Sta/Elev= 30
       0  1173.3      36 1167.18      62 1161.81     129 1150.94   142.4 1147.34
   173.7 1137.16   187.1 1134.99   217.9 1133.39   362.7 1133.28   411.9 1133.89
   426.1 1133.46   431.8 1132.29     435 1131.14   441.4 1130.36   447.7  1130.6
  454.791132.366   466.8  1137.4   478.8 1140.61   515.3 1144.16   519.3 1145.17
   527.4 1149.89   531.5 1151.17   580.1 1160.86   600.3 1166.06   616.4 1167.69
   636.8 1173.35   689.7 1185.02   705.7 1186.56     718 1190.71   756.8 1200.32
#Mann= 9, -1 ,  0
       0    0.05       0     300    0.06       0  388.66    0.05       0
   427.8    0.06       0   431.8   0.045       0  454.79    0.06       0
  547.71    0.05       0  647.71     0.1       0  747.71    0.05       0
Bank Sta=431.8,454.79
XS Rating Curve= 0 ,0
Exp/Cntr(USF)=0,0
Exp/Cntr=0.3,0.1

Type RM Length L Ch R = 1 ,27080   ,330.6,331.2,325.1
BEGIN DESCRIPTION:
Structure 12 XS 1
END DESCRIPTION:
XS GIS Cut Line= 2
 1678909.1213799419788.3548454791679485.83958769419659.284695956
#Sta/Elev= 30
       0 1178.79    76.8 1157.34   130.1 1145.25   162.9 1134.51   171.1 1132.77
   220.3 1128.66   232.6 1129.57   261.3 1129.25   302.3 1130.52   307.1 1130.03
   317.2 1127.95   318.7    1128  321.111130.112   322.8 1131.56   326.9 1136.86
     331 1138.66   350.7 1139.39   359.7 1144.99   367.4 1147.88   376.1 1148.89
   400.9 1155.44   457.9 1167.64   470.3 1171.87   503.1 1172.99   515.4 1179.31
   519.5 1180.67   531.8 1183.69     540 1184.67   552.3 1189.83     591 1201.61
#Mann= 6, -1 ,  0
       0    0.05       0     270     0.1       0   307.1   0.045       0
  321.11     0.1       0     420    0.05       0     570     0.1       0
Bank Sta=307.1,321.11
XS Rating Curve= 0 ,0
Exp/Cntr(USF)=0,0
Exp/Cntr=0.3,0.1

Type RM Length L Ch R = 1 ,26748   ,195.9,191.7,179.3
BEGIN DESCRIPTION:
Structure 11 XS 4
END DESCRIPTION:
XS GIS Cut Line= 2
1679053.55702342420140.7368410041679581.10565044419856.987385305
#Sta/Elev= 30
       0 1183.85    25.6  1177.6      68 1170.88   111.9 1158.84     132 1155.08
   146.8 1150.68   157.3 1144.29   160.9 1143.21   199.9  1139.9   202.9 1139.02
   214.7 1132.47   225.5 1128.66   247.2 1127.18   266.3 1126.73   279.1 1125.26
   285.6 1124.18     289 1124.22  293.131125.304   303.3 1129.85   315.1 1130.57
   325.4 1130.11   329.9 1130.94   334.5  1133.2   348.1 1142.99   365.3 1149.12
   380.1 1150.57   486.4 1173.76   507.1 1180.09   548.4 1195.12     599 1209.57
#Mann= 8, -1 ,  0
       0     0.1       0      20    0.05       0     110    0.06       0
     130    0.05       0     240    0.06       0   279.1   0.045       0
  293.13    0.06       0     360     0.1       0
Bank Sta=279.1,293.13
XS Rating Curve= 0 ,0
Exp/Cntr(USF)=0,0
Exp/Cntr=0.3,0.1

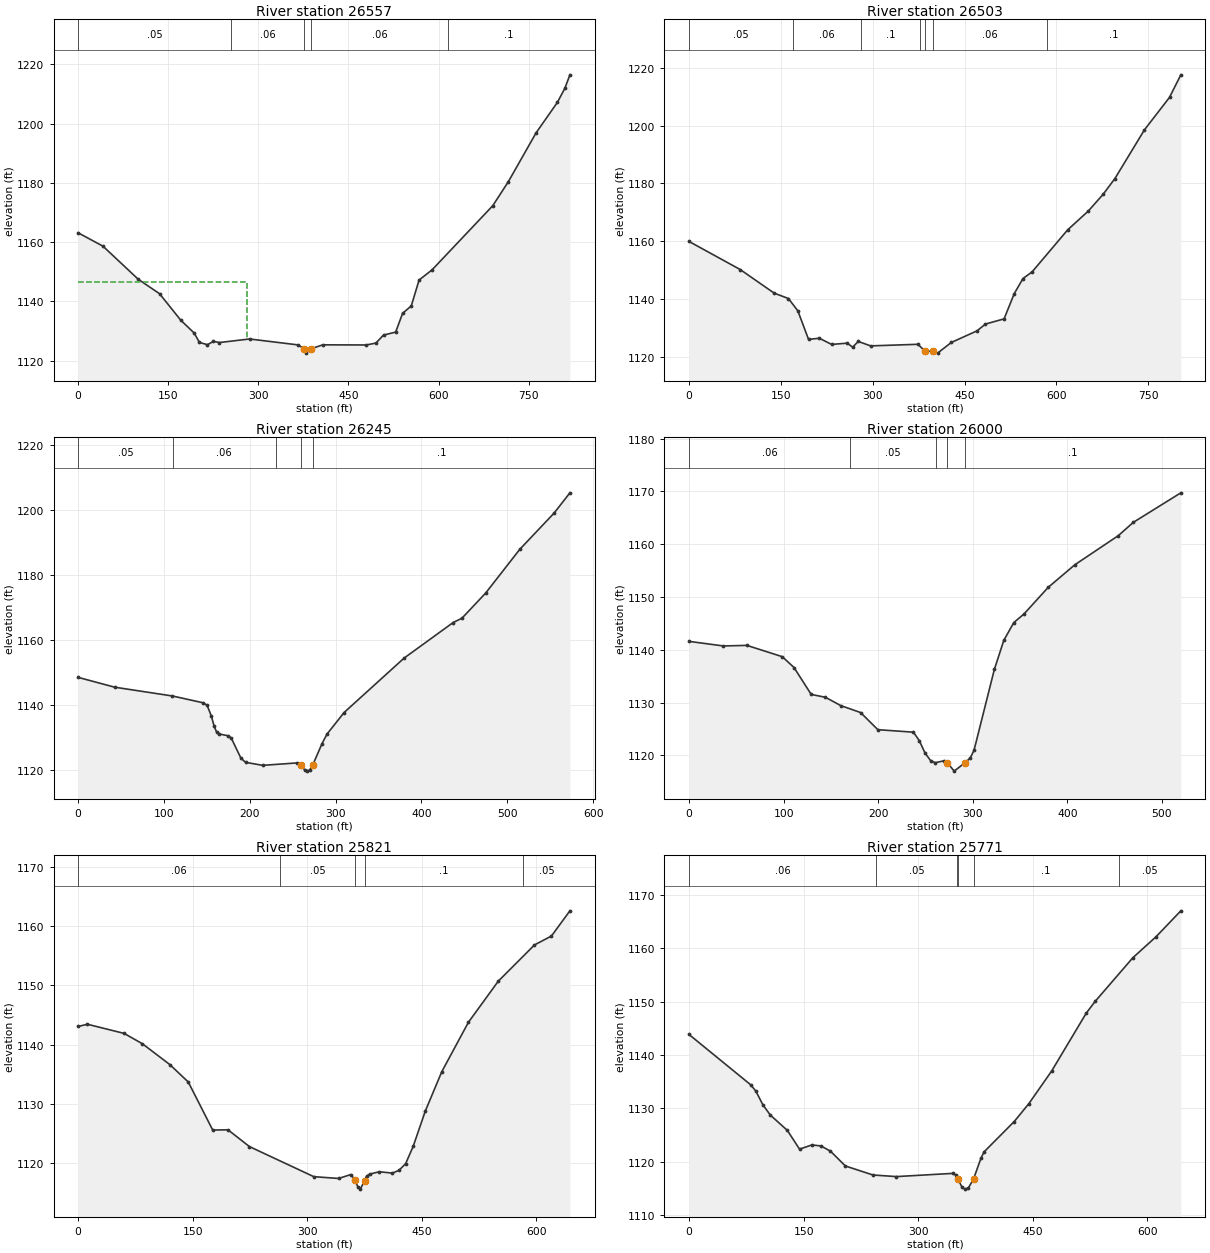
Type RM Length L Ch R = 1 ,26557   ,53.2,54,54.7
BEGIN DESCRIPTION:
Structure 11 XS 3
END DESCRIPTION:
XS GIS Cut Line= 6
1679330.37742218420510.9523034611679431.54939907420298.491151982
1679404.99175514420144.2038872171679377.16946149420094.882548481
1679348.08251813420058.2077068561679617.45290662419879.892097579
#Sta/Elev= 30
       0 1163.14    41.3 1158.64   100.1 1147.47   135.6 1142.59     171 1133.63
   193.2 1129.34     202 1126.16   215.3 1125.41   225.2 1126.53   235.3 1126.14
   285.4 1127.33   366.8 1125.32   375.51124.038   379.4 1122.56   387.7 1124.02
   407.3 1125.36   479.7 1125.31   495.7 1125.95   508.4 1128.65   528.6 1129.65
   540.2    1136   554.6 1138.47   567.6 1147.21   589.2 1150.64   690.3 1172.29
   716.1 1180.34   762.4 1196.86   797.9 1207.14   810.3 1211.89   818.7 1216.42
#Mann= 5, -1 ,  0
       0    0.05       0  255.32    0.06       0   375.5   0.045       0
   387.7    0.06       0  615.64     0.1       0
#XS Ineff= 2 , 0
          281.81 1146.55
Permanent Ineff=
       F       F
Bank Sta=375.5,387.7
XS Rating Curve= 0 ,0
Exp/Cntr(USF)=0,0
Exp/Cntr=0.3,0.1

Type RM Length L Ch R = 1 ,26503   ,254.6,257.4,262.8
BEGIN DESCRIPTION:
Structure 11 XS 2
END DESCRIPTION:
XS GIS Cut Line= 6
1679377.16946149420528.6573994171679494.78188463420327.578095339
1679474.54748925420284.5800051591679455.57774359420154.321084907
1679406.25640485420065.7956051241679645.27520026419903.920442092
#Sta/Elev= 30
       0 1159.97    83.6 1150.27   139.2 1142.11   162.3 1140.27   177.7 1136.03
   195.2 1126.15   212.8 1126.55   232.9 1124.42   258.4 1124.85   267.3 1123.47
   276.3 1125.45   296.6 1123.91   373.8 1124.46  385.551122.105     398 1122.04
     406 1121.41   428.4 1125.09   470.3 1129.09   484.2 1131.45   514.6 1133.24
   531.3    1142   545.4 1147.15   560.4 1149.47   618.3 1163.94   652.3  1170.5
   676.3 1176.23   695.5 1181.65   743.9 1198.52   784.8 1209.72   803.3 1217.51
#Mann= 7, -1 ,  0
       0    0.05       0     170    0.06       0  280.47     0.1       0
  377.73    0.06       0  385.55   0.045       0     398    0.06       0
  584.64     0.1       0
Bank Sta=385.55,398
XS Rating Curve= 0 ,0
Exp/Cntr(USF)=0,0
Exp/Cntr=0.3,0.1

Type RM Length L Ch R = 1 ,26245   ,243.7,245.2,246.1
BEGIN DESCRIPTION:
Structure 11 XS 1
END DESCRIPTION:
XS GIS Cut Line= 2
1679478.61639762420568.867474941 1679821.4891634420109.722068244
#Sta/Elev= 30
       0 1148.48    42.6 1145.45   109.9 1142.74   145.2 1140.67   150.2 1139.92
   155.2  1136.6   158.5  1133.4   161.4 1131.59   164.2 1131.04   175.1 1130.46
   178.5 1129.72   189.7 1123.57   195.1 1122.29   215.1 1121.36     255 1122.11
     260 1121.44   264.2 1119.81   267.1 1119.58     270    1120  273.351121.465
   284.2 1128.07     290    1131   309.9 1137.65   379.8 1154.42     437 1165.39
   447.2 1166.71   474.7 1174.42   514.6 1187.95   554.6 1199.12     573 1205.36
#Mann= 5, -1 ,  0
       0    0.05       0     110    0.06       0     230     0.1       0
     260   0.045       0  273.35     0.1       0
Bank Sta=260,273.35
XS Rating Curve= 0 ,0
Exp/Cntr(USF)=0,0
Exp/Cntr=0.3,0.1

Type RM Length L Ch R = 1 ,26000   ,174.3,178.9,183.3
BEGIN DESCRIPTION:
Structure 10 XS 4
END DESCRIPTION:
XS GIS Cut Line= 3
1679596.99407385420562.2734707251679820.07828291420501.949679501
1680007.87876502420282.280024668
#Sta/Elev= 30
       0 1141.58    36.4 1140.71    61.2 1140.82    98.6 1138.68     111 1136.63
   129.2 1131.53   144.2 1130.99   160.5 1129.41   181.4  1128.1   199.7 1124.85
   237.3 1124.38   243.5 1122.78   249.6 1120.42   255.8 1118.91   260.5  1118.6
   269.8 1118.97  273.241118.586   280.4    1117   291.7 1118.57   297.4 1119.49
   301.4 1120.95   322.9 1136.27   332.9 1141.78   343.5 1145.15   354.3 1146.78
   379.7 1151.79     408 1156.09     454 1161.61   469.8 1164.12   520.1 1169.72
#Mann= 5, -1 ,  0
       0    0.06       0     170    0.05       0   261.1     0.1       0
  273.24   0.045       0   291.7     0.1       0
Bank Sta=273.24,291.7
XS Rating Curve= 0 ,0
Exp/Cntr(USF)=0,0
Exp/Cntr=0.3,0.1

Type RM Length L Ch R = 1 ,25821   ,50,50,50.2
BEGIN DESCRIPTION:
Structure 10 XS 3
END DESCRIPTION:
XS GIS Cut Line= 6
1679591.92149661420597.0896877911679806.25417019420602.134059088
1679892.75621043420610.1013522681679932.59267634420611.239537008
1679980.39643542420599.8576896081680214.41004125420501.925557041
#Sta/Elev= 30
       0 1143.08    12.2 1143.45    60.2 1141.91    84.2 1140.16   120.2 1136.64
   144.2 1133.72   176.2 1125.62   196.2 1125.66   224.3 1122.83   308.6 1117.76
   341.1 1117.46   357.1 1118.12   362.9 1117.12   366.2 1116.03   369.4 1115.66
  375.241117.098   377.6 1117.83   381.7 1118.19   394.3 1118.59   411.5 1118.36
   420.1 1118.83   428.8 1119.95   438.7 1122.87   454.6 1128.83   476.2 1135.47
     511 1143.78   550.1 1150.71   597.5 1156.82   619.7 1158.32   643.9 1162.57
#Mann= 5, -1 ,  0
       0    0.06       0  264.39    0.05       0   362.9   0.045       0
  375.24     0.1       0  582.47    0.05       0
Bank Sta=362.9,375.24
XS Rating Curve= 0 ,0
Exp/Cntr(USF)=0,0
Exp/Cntr=0.3,0.1

Type RM Length L Ch R = 1 ,25771   ,274.2,270.7,264.7
BEGIN DESCRIPTION:
Structure 10 XS 2
END DESCRIPTION:
XS GIS Cut Line= 6
1679611.43653303420643.7311396731679825.76920661 420648.77551097
1679912.27124685 420656.742804151679952.10771276 420657.88098889
1679999.91147184 420646.499141491680233.92507767420548.567008923
#Sta/Elev= 30
       0 1143.84    80.7 1134.41    87.5 1133.22    96.7 1130.65   106.4 1128.74
   128.7 1125.86   144.7 1122.34   160.7 1123.13   172.7 1122.95   185.2 1121.96
   204.7 1119.19   240.8  1117.5   271.5  1117.2   345.2  1117.8   349.3 1117.49
   352.2 1116.71   357.6 1115.16   361.7 1114.85   365.8  1115.1  372.48 1116.74
   382.2 1120.64   386.3 1121.84   425.7 1127.51   444.9 1130.87   474.9 1137.02
   520.2 1147.87   531.7 1150.04   581.1 1158.23   611.5 1162.17   643.9 1167.02
#Mann= 6, -1 ,  0
       0    0.06       0  244.39    0.05       0  351.11     0.1       0
   352.2   0.045       0  372.48     0.1       0  562.47    0.05       0
Bank Sta=352.2,372.48
XS Rating Curve= 0 ,0
Exp/Cntr(USF)=0,0
Exp/Cntr=0.3,0.1