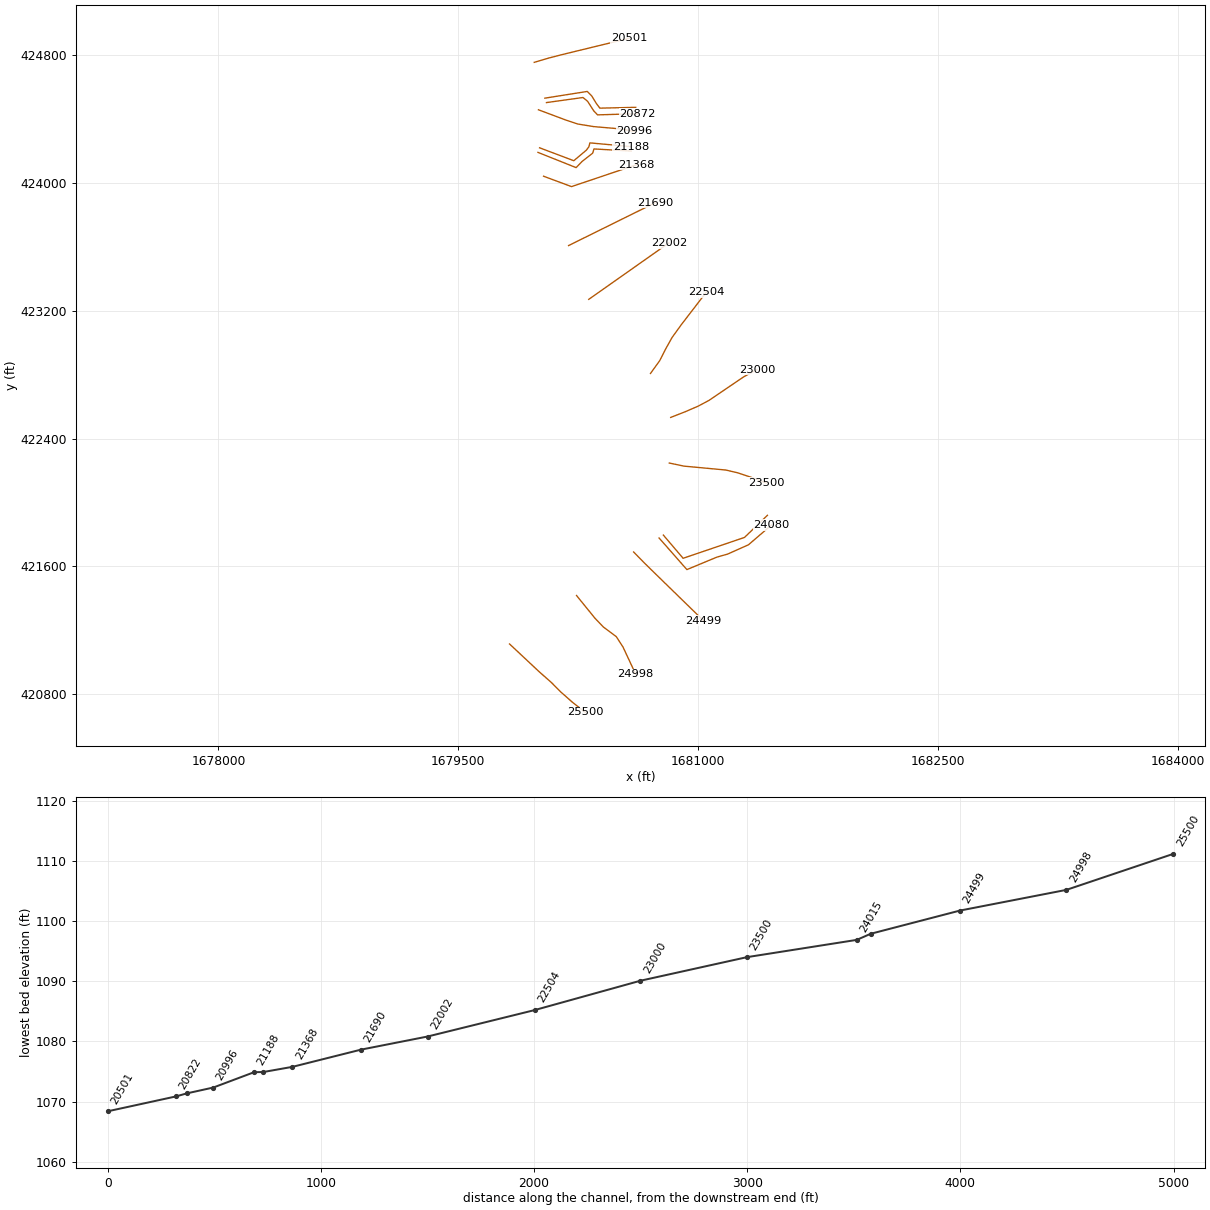
HEC-RAS study SUGARRN.prj: SUGARRN

--- SUGARRN.g01 (geometry) --- (continued)

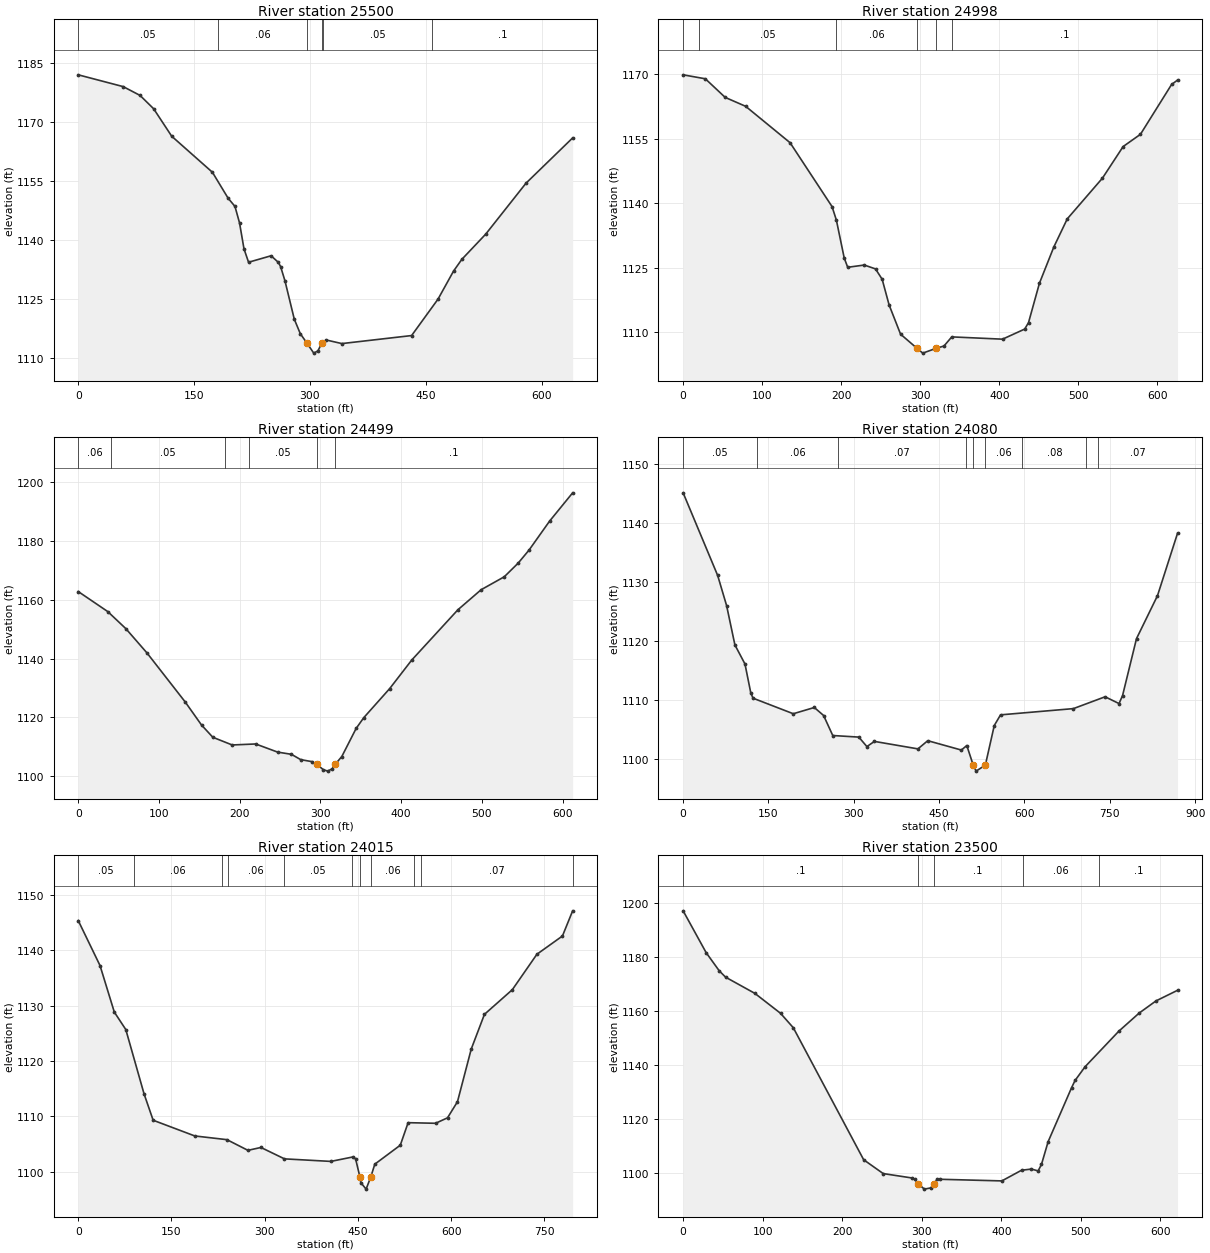
Type RM Length L Ch R = 1 ,25500   ,499.7,502.2,502.4
BEGIN DESCRIPTION:
Structure 10 XS 1
END DESCRIPTION:
XS GIS Cut Line= 6
1679820.57034476 421115.24369742 1680007.7346686420939.945163503
1680082.96023992420873.6113066671680140.32790734 420815.93228817
1680213.37992659420751.0534809231680295.79413185420687.122178346
#Sta/Elev= 30
       0 1181.97    58.2 1178.97      80 1176.73    97.6 1173.34     121 1166.35
   173.7 1157.18     194 1150.59   202.9 1148.49   208.8 1144.31   214.6 1137.68
   220.5 1134.29   249.7 1135.94   259.1 1134.25     262 1133.18   267.6 1129.58
   279.7 1119.81   287.5 1116.11     296 1113.74   304.9 1111.17   310.3 1111.74
  315.411113.738   320.9 1114.52   341.3  1113.6   431.6 1115.64   465.8 1124.91
   485.9 1132.04   496.6 1135.02   527.5 1141.43   579.7  1154.4   640.1 1165.92
#Mann= 6, -1 ,  0
       0    0.05       0  181.29    0.06       0     296   0.045       0
  315.41    0.06       0  316.44    0.05       0  458.08     0.1       0
Bank Sta=296,315.41
XS Rating Curve= 0 ,0
Exp/Cntr(USF)=0,0
Exp/Cntr=0.3,0.1

Type RM Length L Ch R = 1 ,24998   ,499.7,499.4,495.7
XS GIS Cut Line= 6
1680239.37987459421418.5344294161680355.14473492421275.869032338
1680407.73583709421221.0810841771680487.95450868421161.350232512
1680530.03414892421096.4943910841680609.75183725420925.751294255
#Sta/Elev= 30
       0 1169.79    28.1 1168.87    53.2 1164.55    79.1 1162.48   135.3 1154.03
   188.4  1139.2   193.9 1136.05   203.8 1127.27   208.2 1125.11   229.2 1125.63
   243.4 1124.73   251.8 1122.33   260.6 1116.36   275.1 1109.58  296.131106.258
   303.2 1105.18     320 1106.29     330 1106.83   339.9 1108.95   404.1 1108.42
   432.2 1110.77     437 1112.28   450.8 1121.41     469 1129.82     486 1136.35
   530.5  1145.8   556.7 1153.14   578.6 1155.98     618 1167.55   625.5 1168.57
#Mann= 6, -1 ,  0
       0    0.06       0      20    0.05       0  193.74    0.06       0
  296.13   0.045       0     320    0.06       0  339.68     0.1       0
Bank Sta=296.13,320
XS Rating Curve= 0 ,0
Exp/Cntr(USF)=0,0
Exp/Cntr=0.3,0.1

Type RM Length L Ch R = 1 ,24499   ,418.9,418.9,418.9
BEGIN DESCRIPTION:
Structure 9 XS 4
END DESCRIPTION:
XS GIS Cut Line= 6
1680596.50350417421690.6562605051680662.10311051421623.643927336
1680724.53671268421562.3379475921680778.25281259421509.997173011
1680966.26129484421326.8059383331681033.40682983421261.379560009
#Sta/Elev= 30
       0 1162.83    36.6 1156.01    58.9 1150.23    85.2 1141.93   132.5 1125.27
   152.7 1117.43   166.7 1113.26   190.7 1110.64   219.8 1110.98   246.9 1108.22
   264.1 1107.46   275.6 1105.65   289.7 1104.96   295.4 1104.07   303.6 1102.24
   309.1 1101.74   314.7 1102.56  318.631104.155   326.5  1106.7   344.3 1116.28
   353.8 1119.95   385.9 1129.84   413.1 1139.51   470.4 1156.65   499.1 1163.45
   527.8 1167.86     545  1172.5   558.5 1176.95   583.9 1186.78   612.5 1196.42
#Mann= 6, -1 ,  0
       0    0.06       0      40    0.05       0  181.28    0.06       0
  211.28    0.05       0   295.4   0.045       0  318.63     0.1       0
Bank Sta=295.4,318.63
XS Rating Curve= 0 ,0
Exp/Cntr(USF)=0,0
Exp/Cntr=0.3,0.1

Type RM Length L Ch R = 1 ,24080   ,64.9,64.9,64.9
BEGIN DESCRIPTION:
Structure 9 XS 3
END DESCRIPTION:
XS GIS Cut Line= 6
1680756.00611819421777.8719026361680929.82207775421580.480321441
1681117.84314178421658.5261058551681184.90459058421677.472159449
1681314.91514947421735.5865796121681459.19284005421859.495842196
#Sta/Elev= 30
       0 1145.16    60.7 1131.12    76.4    1126      91 1119.32   108.7 1116.08
     119 1111.13   122.9 1110.27   193.6 1107.63   230.6 1108.69   246.9 1107.33
     263 1103.93   308.8 1103.66     323 1102.05   336.2 1102.93   412.7 1101.66
     430 1103.05   489.1 1101.46   498.6 1102.23   509.9  1098.9     515 1097.88
   531.2  1098.9   546.9 1105.63   557.9 1107.44     686  1108.5   741.7 1110.51
   766.2 1109.36   772.4 1110.72   796.9 1120.39   833.8 1127.69     869 1138.28
#Mann= 9, -1 ,  0
       0    0.05       0     130    0.06       0  273.01    0.07       0
  496.59    0.06       0   509.9   0.045       0   531.2    0.06       0
  596.22    0.08       0  708.83     0.1       0  728.83    0.07       0
Bank Sta=509.9,531.2
XS Rating Curve= 0 ,0
Exp/Cntr(USF)=0,0
Exp/Cntr=0.3,0.1

Type RM Length L Ch R = 1 ,24015   ,518.1,515.1,510.1
BEGIN DESCRIPTION:
Structure 9 XS 2
END DESCRIPTION:
XS GIS Cut Line= 4
1680782.51494317421796.2622633451680906.13695569421651.113361719
1681290.20566114421781.6348295041681433.45898546421919.885219813
#Sta/Elev= 30
       0  1145.4      35 1137.28      58 1128.87    76.5 1125.71   105.9 1114.07
   120.5 1109.32   187.5 1106.48   239.2 1105.81     273 1103.88   293.9  1104.4
   331.8 1102.34   406.4 1101.88     442 1102.69   446.2 1102.35  453.131099.074
   454.7 1098.03   463.1 1096.87   470.8 1099.12   477.1 1101.38   518.1 1104.81
   530.7 1108.88   574.9 1108.77   594.1 1109.76   610.1 1112.67   632.3  1122.2
   653.5 1128.46   698.4 1132.92   737.9 1139.32     779 1142.62   795.4 1147.17
#Mann= 11, -1 ,  0
       0    0.05       0      90    0.06       0  230.66    0.07       0
  240.66    0.06       0  330.66    0.05       0  440.66    0.06       0
  453.13   0.045       0   470.8    0.06       0  540.66    0.08       0
  550.66    0.07       0  795.38    0.05       0
Bank Sta=453.13,470.8
XS Rating Curve= 0 ,0
Exp/Cntr(USF)=0,0
Exp/Cntr=0.3,0.1

Type RM Length L Ch R = 1 ,23500   ,491.8,499.9,504.8
BEGIN DESCRIPTION:
Structure 9 XS 1
END DESCRIPTION:
XS GIS Cut Line= 6
1680819.81736201422246.8424840871680912.08128509422227.436026841
1681173.44657601422203.1030702591681247.93330367422185.522724837
1681334.30616242422156.6628744161681425.22986509422122.898506254
#Sta/Elev= 30
       0 1196.95    28.9 1181.49    45.3 1174.79    53.4  1172.4    90.2 1166.41
   122.4 1159.05   138.5 1153.69   226.9 1104.87   251.5 1099.75   287.1 1098.15
   291.2 1097.66   295.2 1096.04   303.2    1094   311.3 1094.45  315.051096.053
   319.3 1097.58   323.3 1097.64   400.6 1097.04   425.3 1100.98   437.7 1101.42
   446.2 1100.74   450.4 1103.14   458.8 1111.58   488.3 1131.56   492.6 1134.19
   505.2 1139.27   547.6 1152.42   573.2 1159.13   594.3 1163.62   621.4 1167.55
#Mann= 5, -1 ,  0
       0     0.1       0   295.2   0.045       0  315.05     0.1       0
  426.79    0.06       0  523.32     0.1       0
Bank Sta=295.2,315.05
XS Rating Curve= 0 ,0
Exp/Cntr(USF)=0,0
Exp/Cntr=0.3,0.1

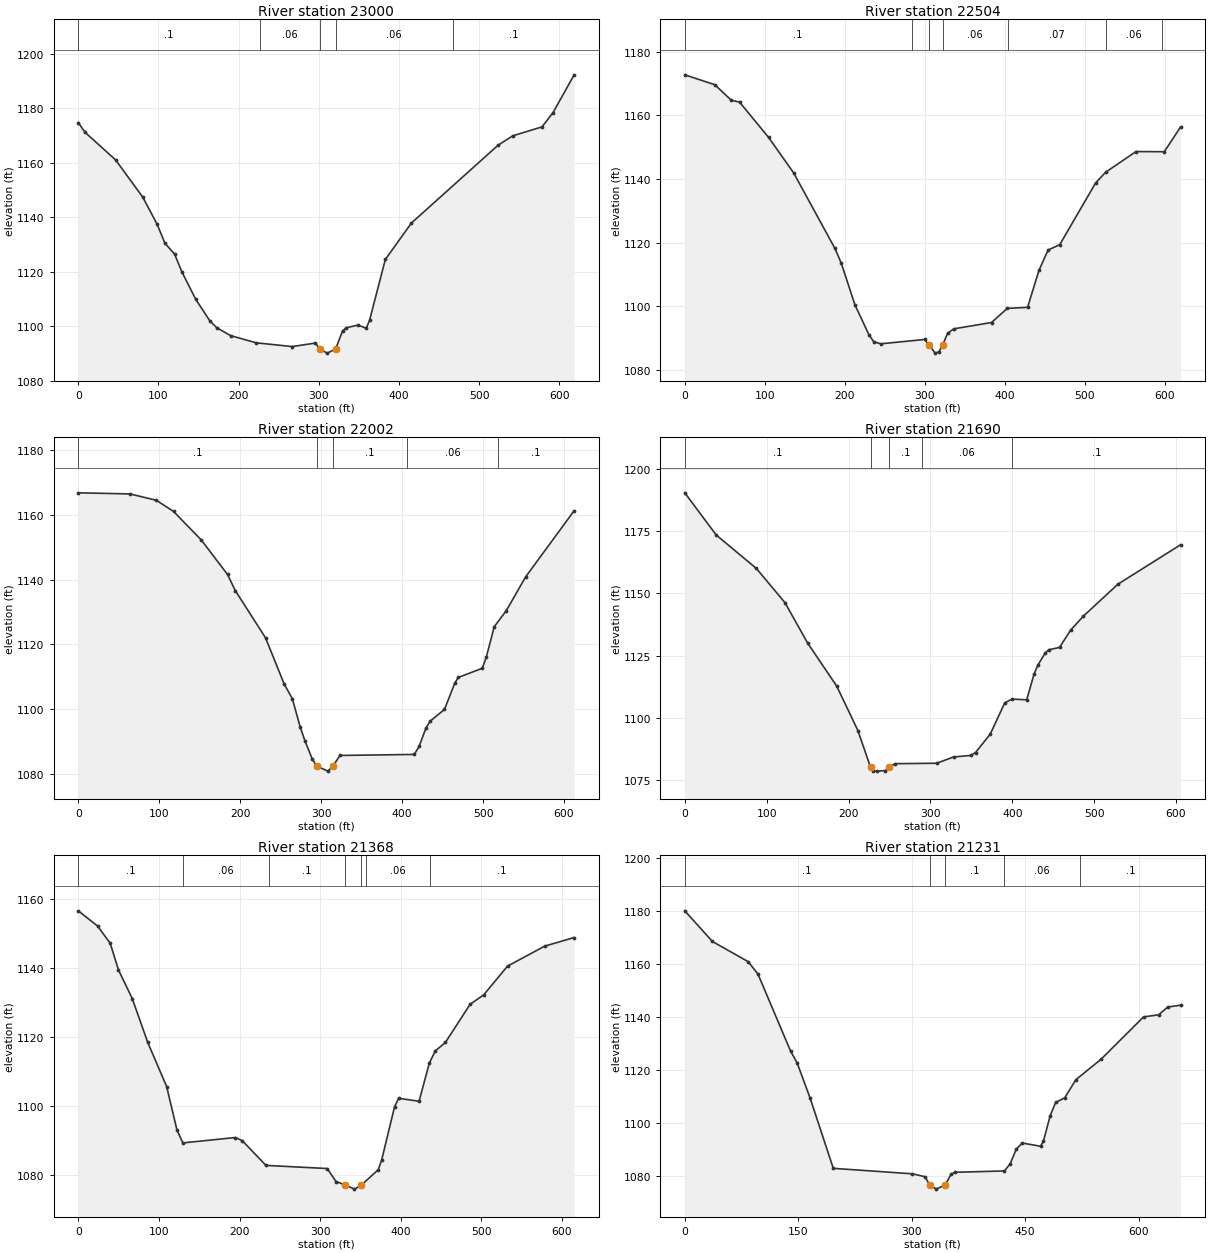
Type RM Length L Ch R = 1 ,23000   ,492.8,496.4,498.1
XS GIS Cut Line= 6
1680828.45743659422532.0784621691680918.12425201422567.131213591
1681000.55978267422602.7420347481681067.55669592422638.288879678
1681284.77443734422785.7751332521681367.24015167422831.167102844
#Sta/Elev= 30
       0 1174.77     8.2 1171.23    46.4 1161.09    80.4 1147.38    98.4 1137.36
     108 1130.47   120.2  1126.4   129.3 1119.85   146.4  1109.9   163.8 1102.05
   172.5 1099.46   189.9 1096.52   221.8 1093.87   266.8 1092.49   295.7 1093.77
   301.5 1091.58   310.5 1090.08  320.941091.585   329.7 1098.26   334.5 1099.41
   348.9 1100.39   359.2 1099.22   363.3 1102.08     383 1124.48   415.6 1137.88
   523.7 1166.46     542 1169.91   578.5 1173.19   592.2 1178.41   618.6 1192.31
#Mann= 5, -1 ,  0
       0     0.1       0  226.07    0.06       0   301.5   0.045       0
  320.94    0.06       0  466.97     0.1       0
Bank Sta=301.5,320.94
XS Rating Curve= 0 ,0
Exp/Cntr(USF)=0,0
Exp/Cntr=0.3,0.1

Type RM Length L Ch R = 1 ,22504   ,503.6,501.9,498
XS GIS Cut Line= 6
 1680702.1502745422807.0582271671680759.88277058422887.304129675
 1680800.2957475422966.3991158461680837.42461026423032.460991591
1680895.98092359423113.5805800111681052.22044051423316.689753845
#Sta/Elev= 30
       0 1172.75    37.6 1169.63    58.2 1164.72    68.4 1164.18   104.7 1153.08
   136.2 1141.85   187.7 1118.12   195.5 1113.56   212.6 1100.45   230.2 1090.96
   236.1 1088.82   244.9 1088.13   299.8  1089.5   305.6  1087.7   312.9  1085.2
   317.8 1085.66  322.251087.744   328.5 1091.45   336.4 1092.85   383.4 1094.83
   403.1 1099.28   428.5  1099.6   442.7 1111.22   454.1 1117.62   468.7 1119.32
   513.6 1138.76     526 1142.09     564 1148.61   599.4 1148.56   619.8 1156.38
#Mann= 7, -1 ,  0
       0     0.1       0  283.46    0.06       0   305.6   0.045       0
  322.25    0.06       0   403.5    0.07       0     526    0.06       0
     596    0.05       0
Bank Sta=305.6,322.25
XS Rating Curve= 0 ,0
Exp/Cntr(USF)=0,0
Exp/Cntr=0.3,0.1

Type RM Length L Ch R = 1 ,22002   ,313.8,312.2,310.5
XS GIS Cut Line= 6
1680315.96469517423270.463140249  1680392.625303423324.427599251
1680525.50233383423417.9657980051680607.26332517423475.543110669
1680740.14330876423569.0832779261680816.80424467423623.048065007
#Sta/Elev= 30
       0 1166.89    63.8 1166.55    96.3 1164.59   117.6 1161.14   151.8 1152.33
   184.3 1141.64   193.9 1136.65   231.3 1122.02   254.2 1107.79   264.3 1103.26
   274.1 1094.42   280.1 1090.05   288.8 1084.67   294.4 1082.35   308.4 1080.81
  314.871082.435   323.1 1085.66     415 1085.97   420.9 1088.43   429.3 1094.05
   434.4 1096.23   452.3 1099.89   464.9 1107.93   469.2 1109.77   499.1 1112.64
     504  1116.1   513.8  1125.5   528.5 1130.38   552.5 1140.87   612.5 1161.36
#Mann= 5, -1 ,  0
       0     0.1       0   294.4   0.045       0  314.87     0.1       0
  406.25    0.06       0  518.75     0.1       0
Bank Sta=294.4,314.87
XS Rating Curve= 0 ,0
Exp/Cntr(USF)=0,0
Exp/Cntr=0.3,0.1

Type RM Length L Ch R = 1 ,21690   ,323,321.6,319.1
XS GIS Cut Line= 2
1680189.76730473  423606.87074391680732.68142574423875.254705608
#Sta/Elev= 30
       0 1190.31    38.3 1173.41    87.4 1159.97   122.4 1146.22   149.9 1130.09
   185.6 1112.72   211.4 1094.93   226.9 1080.14   230.2 1078.77   234.6 1078.63
   244.9 1078.82  249.96 1080.24   256.8 1081.62   307.6 1081.79   328.3 1084.31
   349.4 1084.94   355.1  1086.1     373 1093.43   390.8 1106.03   399.7 1107.54
   417.6 1107.26   426.5 1117.47     431 1121.03   439.9 1125.87   444.4 1127.32
   457.7 1128.27   471.1 1135.15   486.8 1140.82   529.1 1153.67   605.6 1169.48
#Mann= 5, -1 ,  0
       0     0.1       0   226.9   0.045       0  249.96     0.1       0
     290    0.06       0     400     0.1       0
Bank Sta=226.9,249.96
XS Rating Curve= 0 ,0
Exp/Cntr(USF)=0,0
Exp/Cntr=0.3,0.1

Type RM Length L Ch R = 1 ,21368   ,133.7,136.7,139.6
BEGIN DESCRIPTION:
Structure 8 XS 4
END DESCRIPTION:
XS GIS Cut Line= 3
1680033.39648318424040.5673712161680208.20589752423975.642599682
1680614.51054801424112.542410349
#Sta/Elev= 30
       0 1156.69    23.9 1152.25    39.5 1147.28    49.8 1139.51    66.9 1131.18
    86.1 1118.43   109.6 1105.58   122.4 1092.94   129.7 1089.21   194.8 1090.77
   203.3 1089.88   232.8 1082.67   308.8 1081.76   319.7 1077.98   331.3 1076.97
   342.6 1075.77     351 1076.91   372.1 1081.41   376.3 1084.17   392.3 1099.64
   397.4 1102.17   422.8 1101.32   435.4 1112.34   442.8 1115.93   455.5 1118.43
   486.1 1129.52     503 1132.26   532.5 1140.61   578.6 1146.42   615.2 1148.93
#Mann= 7, -1 ,  0
       0     0.1       0     130    0.06       0  236.48     0.1       0
   331.3   0.045       0     351     0.1       0  356.48    0.06       0
  436.48     0.1       0
Bank Sta=331.3,351
XS Rating Curve= 0 ,0
Exp/Cntr(USF)=0,0
Exp/Cntr=0.3,0.1

Type RM Length L Ch R = 1 ,21231   ,42.4,43.2,43
BEGIN DESCRIPTION:
Structure 8 XS 3
END DESCRIPTION:
XS GIS Cut Line= 6
1679998.21081298424189.7351492881680236.88815297424094.469086545
1680274.78970481424133.3950046551680340.34914584424184.613317958
1680348.54407597424211.2468408761680581.07521837424197.930079417
#Sta/Elev= 30
       0 1180.17    36.5 1168.58    83.9 1160.92    96.8 1156.21   139.9 1127.07
   148.5 1122.66   165.7 1109.32   196.3 1082.77     301  1080.7   317.5 1079.61
   323.7 1076.54   332.6 1074.91   344.5 1076.63   351.9 1080.48   357.1 1081.28
   422.6 1081.79   430.2 1084.53   438.2 1090.04   446.2 1092.34   470.3 1091.13
   474.2 1093.11     483 1102.63   490.3 1107.71   502.3 1109.44     517 1116.29
   550.4 1124.06   606.5 1140.04   626.5 1140.85   638.5  1143.8   655.5 1144.47
#Mann= 5, -1 ,  0
       0     0.1       0   323.7   0.045       0   344.5     0.1       0
  422.59    0.06       0  522.59     0.1       0
Bank Sta=323.7,344.5
XS Rating Curve= 0 ,0
Exp/Cntr(USF)=0,0
Exp/Cntr=0.3,0.1

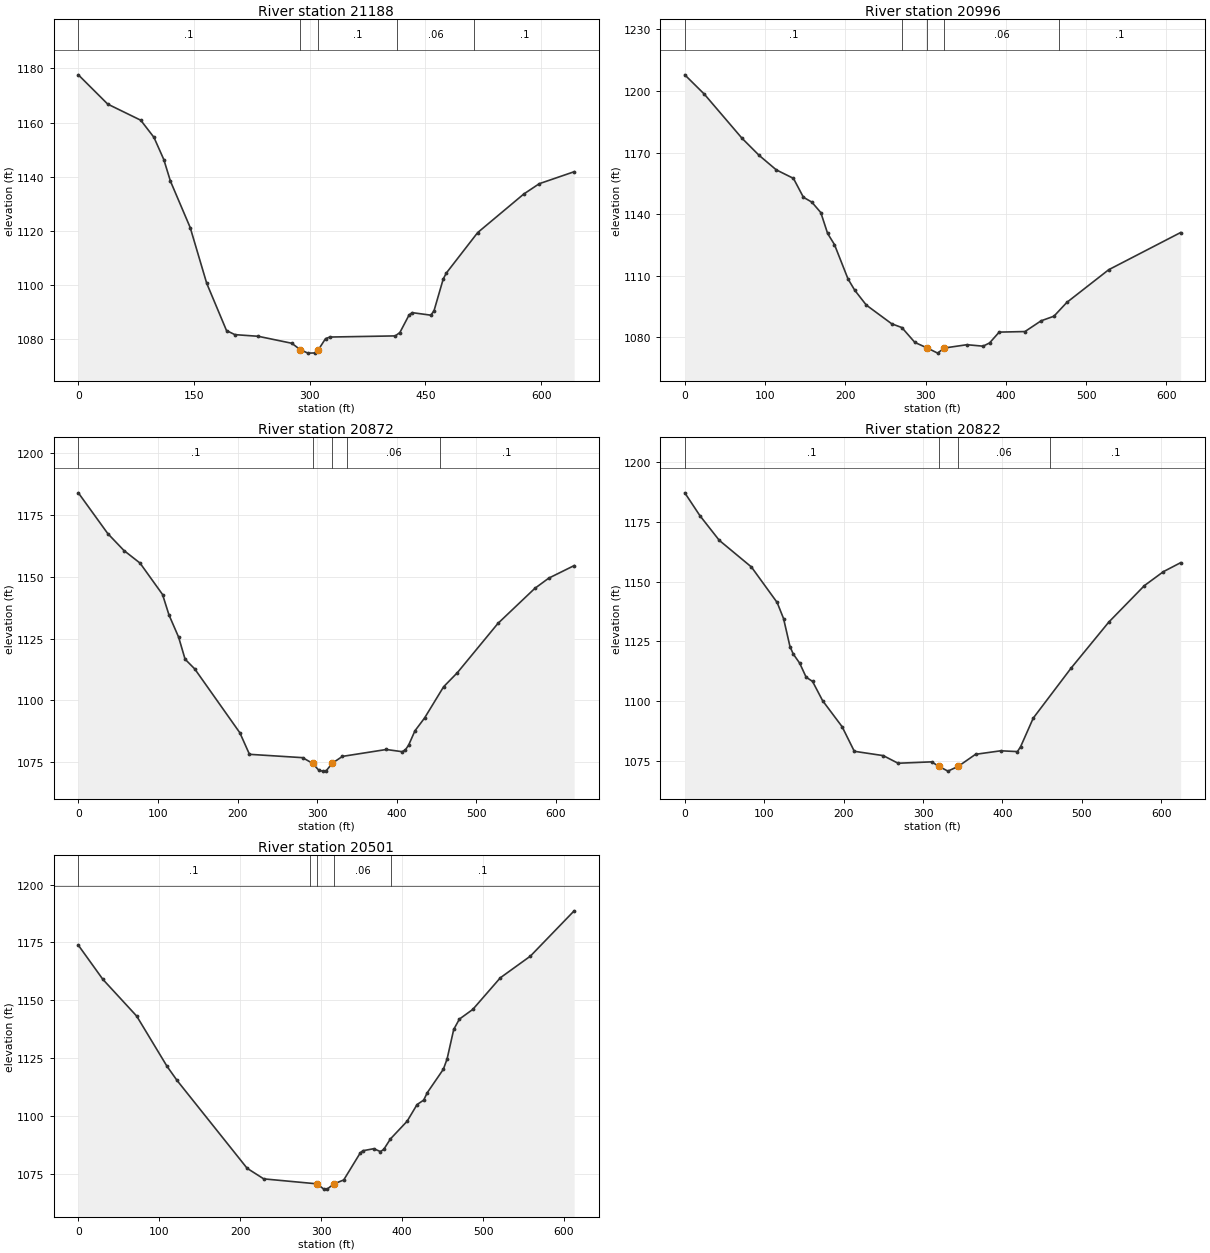
Type RM Length L Ch R = 1 ,21188   ,201,191.7,182.7
BEGIN DESCRIPTION:
Structure 8 XS 2
END DESCRIPTION:
XS GIS Cut Line= 6
1680008.45447564424218.4174047381680222.54702524424137.492469719
1680301.42322773424204.0762770131680316.78872172424224.563602334
1680322.93491932 424249.148392721680581.07521837  424225.5879686
#Sta/Elev= 30
       0 1177.64    38.1 1166.83    80.9 1160.88      98 1154.56   110.8 1146.35
   119.4 1138.37     145 1121.25   166.4 1100.67   192.1  1083.2   202.9 1081.71
   233.1  1081.1   276.7 1078.52  287.381076.207   297.5 1074.88   306.3 1074.94
   311.2 1076.16   320.4 1080.22     326 1080.82   410.9 1081.24   416.8 1082.49
   428.8 1089.01   432.8 1089.83   456.9 1088.89     461 1090.48     473 1102.26
     477 1104.45   517.6 1119.38   577.4 1133.63   597.5 1137.44   642.7 1141.86
#Mann= 5, -1 ,  0
       0     0.1       0  287.38   0.045       0   311.2     0.1       0
  413.46    0.06       0  513.46     0.1       0
Bank Sta=287.38,311.2
XS Rating Curve= 0 ,0
Exp/Cntr(USF)=0,0
Exp/Cntr=0.3,0.1

Type RM Length L Ch R = 1 ,20996   ,132.7,124.1,113.6
BEGIN DESCRIPTION:
Structure 8 XS 1
END DESCRIPTION:
XS GIS Cut Line= 6
1680001.39609858424456.1198896771680174.12869276424391.423824832
1680246.87362601424367.1725610051680345.85177451424351.018065751
1680507.75138509424337.0633692591680600.35553059 424321.06832251
#Sta/Elev= 30
       0 1207.91    24.3 1198.51    71.3 1177.01    92.7 1168.65     114 1161.61
   135.4 1157.47   147.8 1148.27   158.3  1145.9   169.5  1140.8     178 1130.62
   186.5 1125.23   203.4 1108.47   211.8 1102.96   226.2 1095.74   257.9 1086.61
   270.5 1084.79   286.7 1077.55  301.89 1074.88   315.1 1072.33   323.2 1074.81
   351.6 1076.43   371.7 1075.72   379.8 1077.29   391.8 1082.57   423.9 1082.84
     444 1088.07     460 1090.31   476.1 1097.04   528.3 1112.97   617.9 1131.08
#Mann= 5, -1 ,  0
       0     0.1       0  271.13    0.06       0  301.89   0.045       0
   323.2    0.06       0  466.42     0.1       0
Bank Sta=301.89,323.2
XS Rating Curve= 0 ,0
Exp/Cntr(USF)=0,0
Exp/Cntr=0.3,0.1

Type RM Length L Ch R = 1 ,20872   ,48.7,50.1,48.7
BEGIN DESCRIPTION:
Structure 7 XS 3
END DESCRIPTION:
XS GIS Cut Line= 6
1680051.47785881424501.1424941711680279.91153614424532.897848418
1680308.59379159424509.337424299 1680347.5197097424448.899814601
1680371.08013382424424.3150242161680620.00113648424431.485588078
#Sta/Elev= 30
       0 1184.07      37 1167.56    57.3 1160.71    77.5 1155.62   105.8 1142.89
   113.9  1134.6     126 1125.61   134.1 1116.69   146.2 1112.77   202.9  1086.9
     215 1078.17   281.8 1076.81   294.2 1074.53   302.2 1071.69   306.9 1071.36
   311.6 1071.58  319.131074.585   331.8 1077.33   386.9 1080.12   406.9 1079.23
   410.9 1080.01   414.9 1081.86   422.9  1087.7   434.9 1092.84   458.9 1105.53
   476.2 1111.24   527.1 1131.17   573.4 1145.35     591 1149.52   622.9  1154.6
#Mann= 5, -1 ,  0
       0     0.1       0   294.2   0.045       0  319.13     0.1       0
  337.92    0.06       0  453.86     0.1       0
Bank Sta=294.2,319.13
XS Rating Curve= 0 ,0
Exp/Cntr(USF)=0,0
Exp/Cntr=0.3,0.1

Type RM Length L Ch R = 1 ,20822   ,311,321.2,336.1
BEGIN DESCRIPTION:
Structure 7 XS 2
END DESCRIPTION:
XS GIS Cut Line= 6
1680041.23419615424528.8003833541680306.54505906424570.799400263
1680334.20294825424543.1415110791680363.90956996424494.996296574
1680385.42126155424466.3140411241680609.75747382424471.435872455
#Sta/Elev= 30
       0 1187.01    19.1 1177.45    43.4 1167.19    83.9 1156.06   116.3 1141.25
   124.4 1134.52   132.5 1122.83   136.6 1119.74   144.7 1115.92   152.8 1110.08
   160.9  1108.3   173.6 1100.25   198.1 1089.42   213.5 1079.14     250 1077.33
   268.6 1074.15   310.8 1074.73   320.2 1072.82   331.4 1070.86  344.431072.861
   366.2 1077.88     398 1079.35   418.9 1079.01   422.9 1081.01   438.9    1093
   486.6 1113.88     534 1133.05   578.9 1148.29   602.9 1154.13   624.5 1157.85
#Mann= 4, -1 ,  0
       0     0.1       0   320.2   0.045       0  344.43    0.06       0
  460.15     0.1       0
Bank Sta=320.2,344.43
XS Rating Curve= 0 ,0
Exp/Cntr(USF)=0,0
Exp/Cntr=0.3,0.1

Type RM Length L Ch R = 1 ,20501   ,490.3,498.9,508.6
BEGIN DESCRIPTION:
Structure 7 XS 1
END DESCRIPTION:
XS GIS Cut Line= 6
1679974.95356618424752.7925246661680064.96322867424779.406644672
1680149.69304609424801.2842255831680392.60988308424860.373346254
1680477.63071042424881.0537510961680568.72436026424903.212499425
#Sta/Elev= 30
       0 1173.79    30.4 1158.99    72.1 1143.15   109.5  1121.5   121.9 1115.38
   208.6 1077.37   229.1 1072.81     295 1070.66   303.2  1068.4   307.4 1068.38
   315.6 1070.61   327.9 1072.34   348.5 1084.13   351.6 1084.97     365 1085.85
   373.2 1084.61   377.3 1085.52   385.6 1090.07   406.2 1097.71   418.5 1104.92
   426.7 1106.85   431.1 1110.04     451 1120.19   455.6 1124.61   463.8 1137.39
   470.8 1141.85   487.4 1146.05   521.4 1159.71   558.5 1169.06   612.6 1188.64
#Mann= 5, -1 ,  0
       0     0.1       0  286.37    0.06       0     295   0.045       0
   315.6    0.06       0  386.37     0.1       0
Bank Sta=295,315.6
XS Rating Curve= 0 ,0
Exp/Cntr(USF)=0,0
Exp/Cntr=0.3,0.1