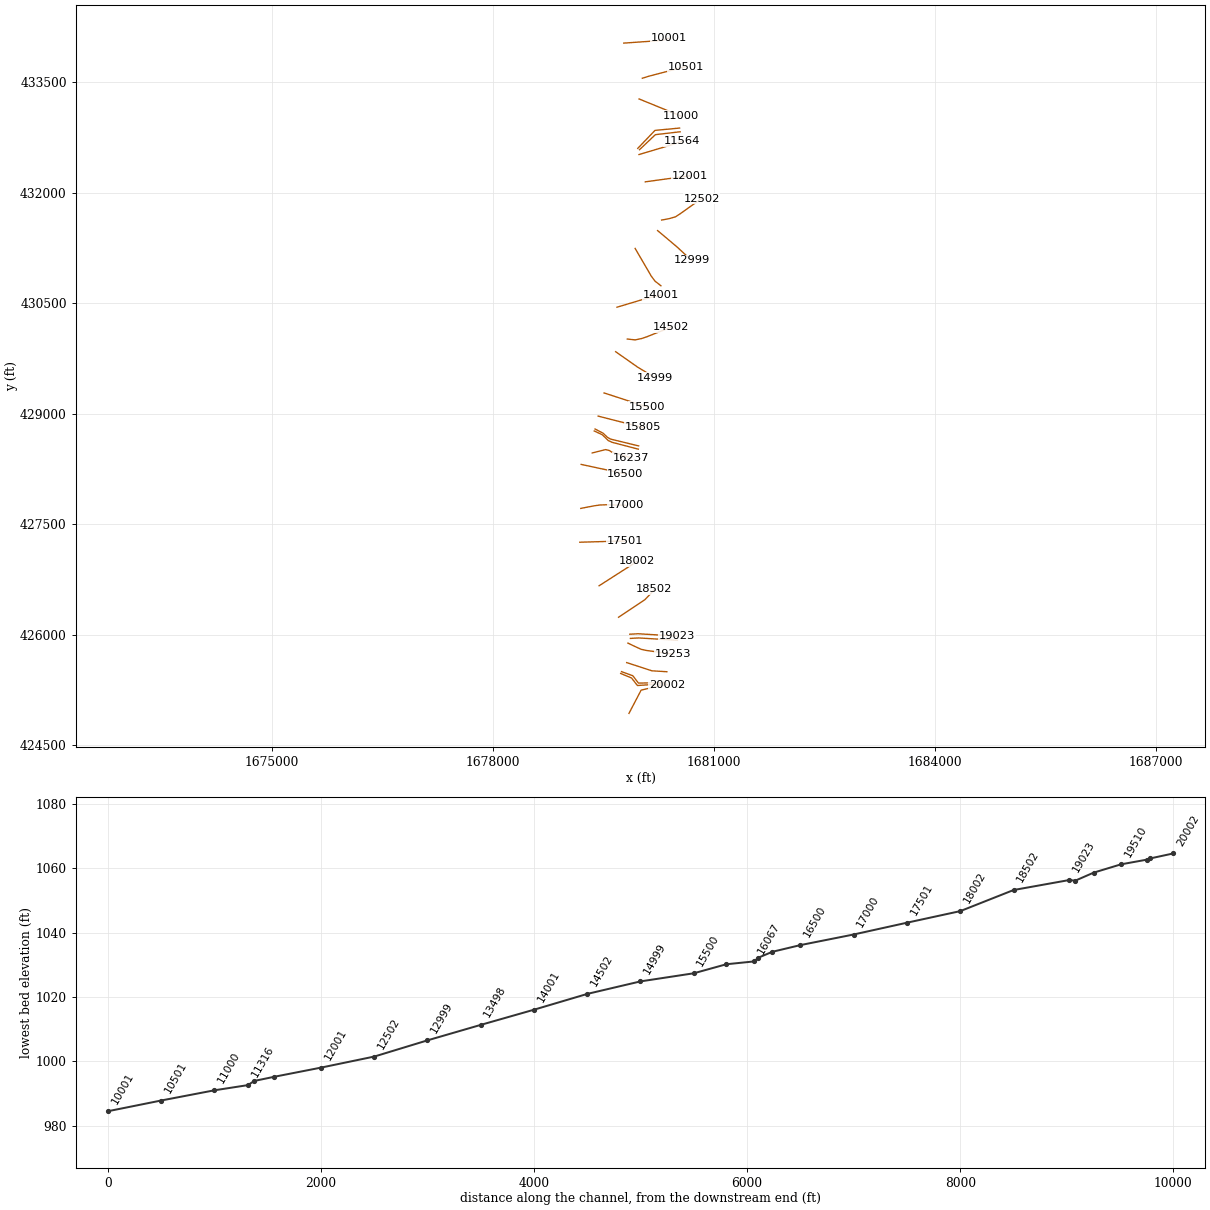
HEC-RAS study SUGARRN.prj: SUGARRN

--- SUGARRN.g01 (geometry) --- (continued)

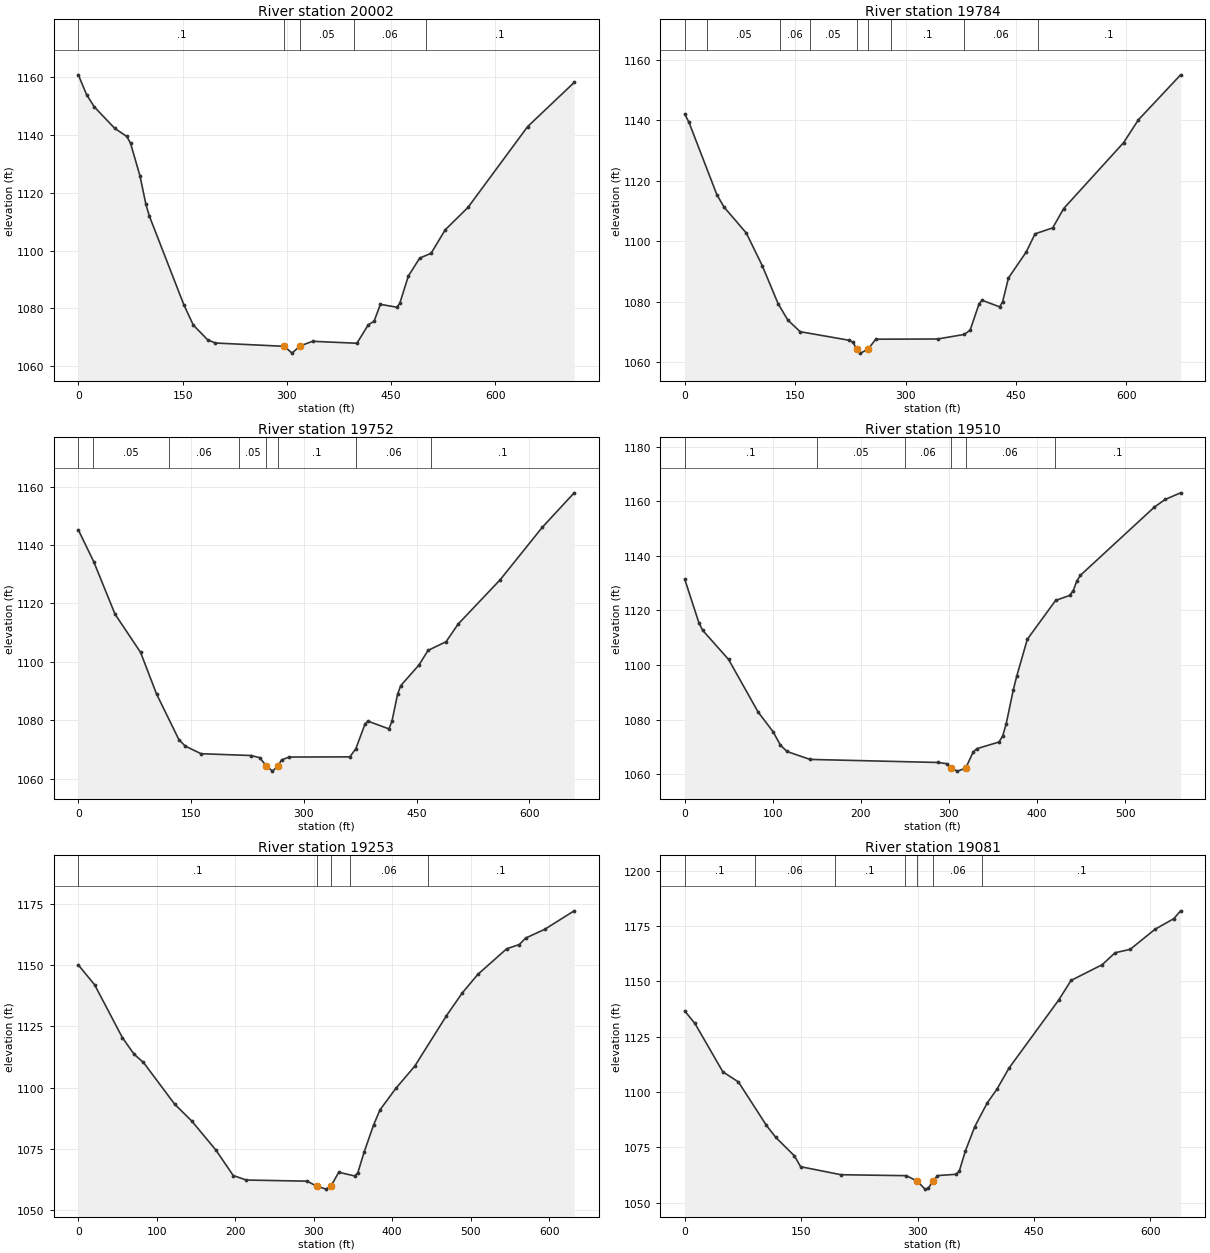
Type RM Length L Ch R = 1 ,20002   ,233.5,218.3,197.6
BEGIN DESCRIPTION:
Structure 6 XS 4
END DESCRIPTION:
XS GIS Cut Line= 6
1679847.76746884424929.9703199271679931.75877067425090.585156173
1680012.85342476425245.6612895881680123.97853059425271.875804082
1680243.15972267425297.0411080871680361.65456443425321.355035841
#Sta/Elev= 30
       0 1160.71    11.9 1153.85    22.9 1149.65    52.5 1142.19    69.8  1139.4
    75.1 1137.06    88.7 1125.76      97 1116.16   102.2 1111.88   151.9 1081.18
   165.4 1074.23   185.9 1069.17     197 1068.04   296.3 1066.89   307.4 1064.54
   318.9 1067.01   336.9 1068.63   400.7 1067.95   417.1 1074.35   425.4 1075.54
   434.5  1081.4   458.2 1080.41   462.3  1081.7   474.7 1091.17     491 1097.38
   507.4 1099.04   527.8 1107.17   560.5  1114.9   646.3 1142.83   713.2 1158.07
#Mann= 5, -1 ,  0
       0     0.1       0   296.3   0.045       0   318.9    0.05       0
  396.25    0.06       0  500.43     0.1       0
Bank Sta=296.3,318.9
XS Rating Curve= 0 ,0
Exp/Cntr(USF)=0,0
Exp/Cntr=0.3,0.1

Type RM Length L Ch R = 1 ,19784   ,31.8,31.8,31.7
BEGIN DESCRIPTION:
Structure 6 XS 3
END DESCRIPTION:
XS GIS Cut Line= 4
 1679734.9486826425472.2417143951679882.45742491425410.779738432
1679962.35799367425308.3431118261680345.47097717425333.952268477
#Sta/Elev= 30
       0 1142.05     5.6 1139.42    43.5 1115.47    53.3 1111.33    83.6 1102.73
   105.3  1091.9   126.9 1079.29   139.9 1073.96   156.7 1070.08   223.5 1067.23
   228.6 1066.53   233.7 1064.25   238.7 1062.98   248.9 1064.26   259.5 1067.59
   343.6 1067.66   379.7 1069.17   387.7 1070.59   399.7 1079.21   403.7  1080.5
   427.8  1078.3   431.8 1079.93   439.8 1087.87   463.9 1096.46   475.9 1102.47
   499.9 1104.44   514.8 1110.84   596.2 1132.65   616.2 1140.17   673.7  1155.1
#Mann= 9, -1 ,  0
       0     0.1       0      30    0.05       0     130    0.06       0
   169.8    0.05       0   233.7   0.045       0   248.9    0.05       0
   279.8     0.1       0  379.71    0.06       0  479.71     0.1       0
Bank Sta=233.7,248.9
XS Rating Curve= 0 ,0
Exp/Cntr(USF)=0,0
Exp/Cntr=0.3,0.1

Type RM Length L Ch R = 1 ,19752   ,235.6,242,245.6
BEGIN DESCRIPTION:
Structure 6 XS 2
END DESCRIPTION:
XS GIS Cut Line= 4
1679746.21671153425496.8265047811679899.87165144425441.510726413
1679976.69912139425341.1228323391680346.49534344425349.317762468
#Sta/Elev= 30
       0 1145.17    20.5 1134.27    48.8 1116.34    82.8 1103.25     104 1089.03
   133.8 1073.37   142.3 1071.16   163.3 1068.56   229.8 1067.94   241.2  1067.2
   250.2 1064.38   258.3  1062.6  265.661064.421   270.3 1066.42   280.4 1067.42
   361.2 1067.48   369.2  1070.3   381.2 1078.59   385.2 1079.71   413.2 1077.06
   417.2 1079.68   424.7 1088.92   428.8 1091.83   453.4 1099.01   465.2 1103.92
   489.2 1106.89   505.2 1112.91   561.2 1128.11   617.2 1146.05   659.6 1157.85
#Mann= 8, -1 ,  0
       0     0.1       0      20    0.05       0     120    0.06       0
  213.31    0.05       0   250.2   0.045       0  265.66     0.1       0
  369.72    0.06       0  469.72     0.1       0
Bank Sta=250.2,265.66
XS Rating Curve= 0 ,0
Exp/Cntr(USF)=0,0
Exp/Cntr=0.3,0.1

Type RM Length L Ch R = 1 ,19510   ,255.5,257.2,258.3
BEGIN DESCRIPTION:
Structure 6  XS 1
END DESCRIPTION:
XS GIS Cut Line= 3
1679816.89798389425619.7504567081680159.03631675425508.094533707
1680361.86083743425495.802138514
#Sta/Elev= 30
       0 1131.35      16 1115.51    20.2 1112.76    49.7 1102.06    83.3 1082.77
   100.2 1075.61   108.6 1070.67   116.1 1068.34   142.2 1065.44   287.3 1064.32
   297.9 1063.86   302.1  1062.2   309.6 1061.15     319  1062.2   327.4 1068.11
   331.6 1069.36   356.8 1071.81     361 1074.01     365 1078.46     373 1090.81
     377 1095.96     389 1109.45   421.1 1123.65   437.1 1125.51   441.1 1127.21
   445.1 1130.69   449.1 1132.81   533.3 1157.85   545.6 1160.66   563.1 1163.07
#Mann= 6, -1 ,  0
       0     0.1       0     150    0.05       0     250    0.06       0
   302.1   0.045       0     319    0.06       0   419.9     0.1       0
Bank Sta=302.1,319
XS Rating Curve= 0 ,0
Exp/Cntr(USF)=0,0
Exp/Cntr=0.3,0.1

Type RM Length L Ch R = 1 ,19253   ,171.5,172.3,173.4
BEGIN DESCRIPTION:
Structure 5 XS 4
END DESCRIPTION:
XS GIS Cut Line= 6
1679833.32441782425884.6917159261679927.99384792425839.102568254
1680014.78402866425799.8001534341680088.34621749425783.896641925
1680348.40770524425748.2008471791680441.28678458425735.452185005
#Sta/Elev= 30
       0 1149.99    20.9 1141.82    56.1 1120.36    71.1 1113.55      83 1110.23
   122.8  1093.2   144.7  1086.3   175.5 1074.42   197.4 1064.12     214 1062.28
   291.5 1061.82   303.6 1059.82   315.8 1058.57   322.11059.888   331.9 1065.45
   352.1 1063.94   356.1 1065.16   364.2 1073.64   376.3 1084.74   384.4 1090.86
   404.6 1099.63   428.8 1108.73   469.2  1129.3   489.4  1138.6   509.1 1146.12
   545.9 1156.57     562  1158.3   570.1 1160.94   594.4  1164.5   631.9 1172.04
#Mann= 5, -1 ,  0
       0     0.1       0   303.6   0.045       0   322.1     0.1       0
  345.61    0.06       0  445.61     0.1       0
Bank Sta=303.6,322.1
XS Rating Curve= 0 ,0
Exp/Cntr(USF)=0,0
Exp/Cntr=0.3,0.1

Type RM Length L Ch R = 1 ,19081   ,57.9,57.9,57.5
BEGIN DESCRIPTION:
Structure 5 XS 3
END DESCRIPTION:
XS GIS Cut Line= 3
1679867.07148519425948.1779706681679980.56881456425954.483062247
1680505.05539587425922.729055622
#Sta/Elev= 30
       0 1136.54    13.1 1130.92    49.1 1109.07    69.1 1104.52   105.2  1084.9
   117.2 1079.48   141.3 1071.11   149.3 1066.21   201.4 1062.59   285.5 1062.16
  299.79 1059.67   309.6 1056.08   313.6 1056.45  320.181059.687   325.6 1062.19
   349.6 1062.79   353.7 1064.12   361.7 1073.34   373.7 1084.27   389.7 1094.96
   402.3 1101.22   417.8 1110.72   481.9 1141.51   497.9 1150.39     538 1157.49
   554.7  1162.9   574.1 1164.43   606.1  1173.5   630.2 1178.27   639.1 1181.83
#Mann= 7, -1 ,  0
       0     0.1       0      90    0.06       0  193.67     0.1       0
  283.67    0.06       0  299.79   0.045       0  320.18    0.06       0
  383.67     0.1       0
Bank Sta=299.79,320.18
XS Rating Curve= 0 ,0
Exp/Cntr(USF)=0,0
Exp/Cntr=0.3,0.1

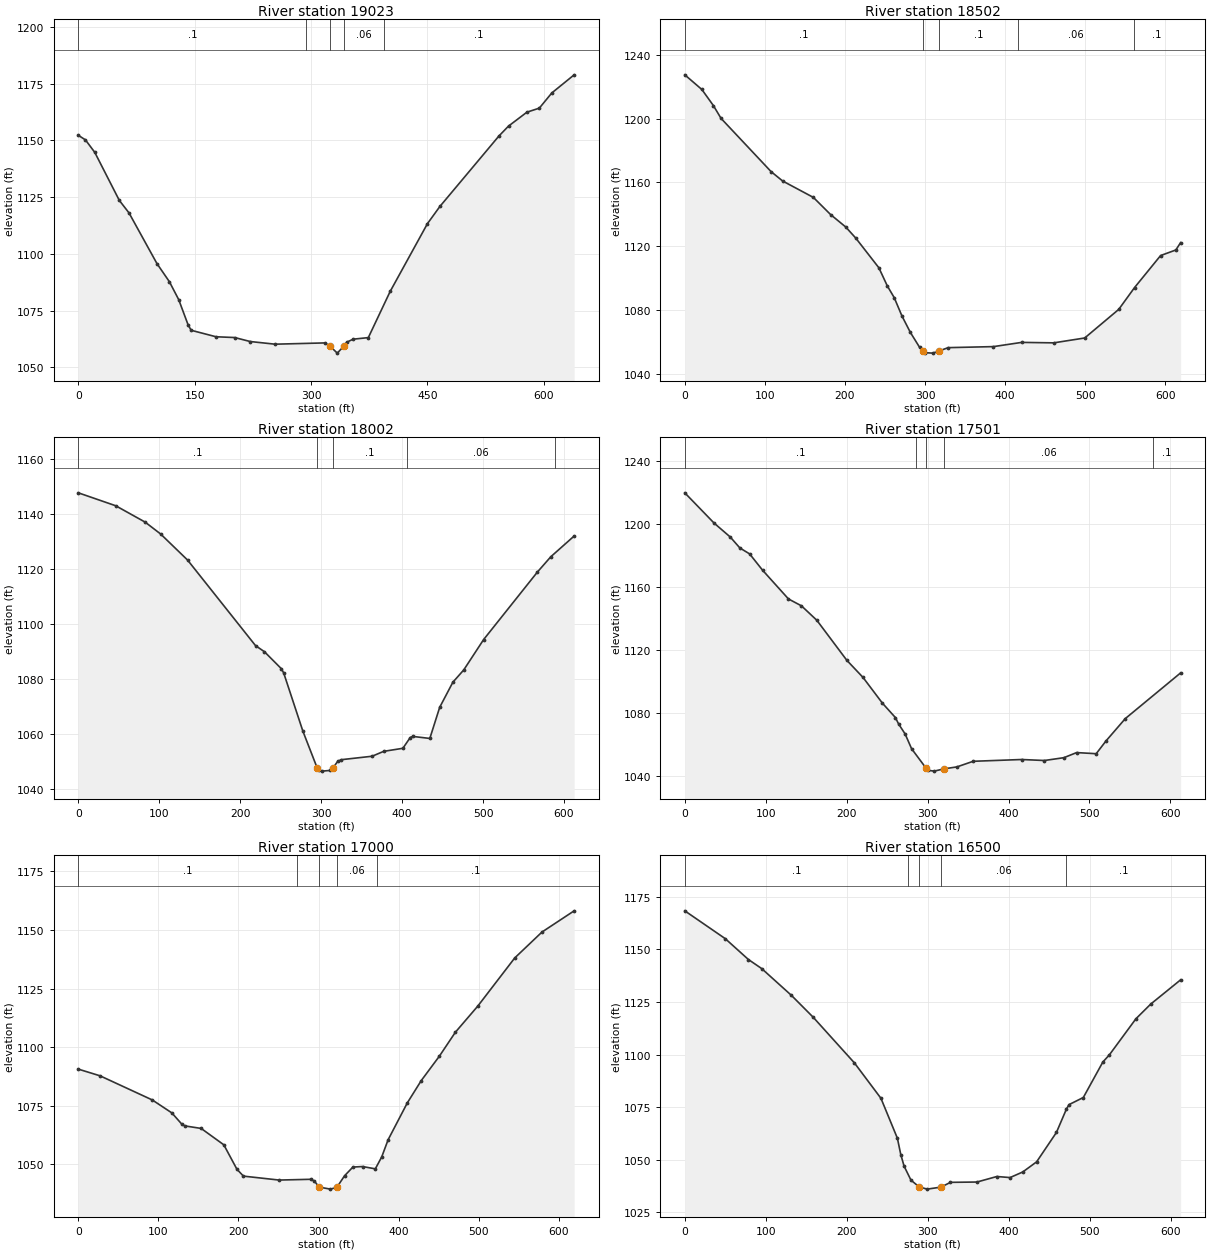
Type RM Length L Ch R = 1 ,19023   ,512.7,520.9,524.6
BEGIN DESCRIPTION:
Structure 5 XS 2
END DESCRIPTION:
XS GIS Cut Line= 3
1679858.92748967426005.1793937541679972.42481904426011.484485333
1680496.91140035425979.730478709
#Sta/Elev= 30
       0 1152.26     9.2 1150.23    21.2 1144.74    52.8 1123.59    65.3 1118.07
   101.3 1095.75   117.4 1087.73   129.4 1079.83   141.4 1068.81   145.4 1066.34
   177.5 1063.48   201.5 1063.14   221.6 1061.38   253.6 1060.21   317.7 1060.77
     324 1059.46   333.8 1056.27  342.561059.478   345.8 1061.06   354.2 1062.41
   373.8 1063.11   401.9 1083.43     450 1113.33     466 1120.89   542.1 1151.94
   554.5 1156.32   578.2 1162.45   594.2 1164.23   610.3 1170.92   639.1 1178.91
#Mann= 5, -1 ,  0
       0     0.1       0  293.67    0.06       0     324   0.045       0
  342.56    0.06       0  393.67     0.1       0
Bank Sta=324,342.56
XS Rating Curve= 0 ,0
Exp/Cntr(USF)=0,0
Exp/Cntr=0.3,0.1

Type RM Length L Ch R = 1 ,18502   ,499.9,500,499.4
BEGIN DESCRIPTION:
Structure 5 XS 1
END DESCRIPTION:
XS GIS Cut Line= 6
 1679706.4278565426235.5408715011679784.43294984426287.544048339
1680002.84557076426433.1533371661680064.84150976426475.367491588
1680126.90897092426539.7869821791680192.80811734426612.980077252
#Sta/Elev= 30
       0 1227.33    21.3 1218.16    35.7 1208.09    45.3 1200.06   107.8 1166.74
   122.2 1160.89   160.6 1150.61   182.1 1139.88     201  1132.1   213.6 1125.11
   242.4 1106.56   252.9 1095.23   261.5 1087.94   271.2 1076.41   281.7 1066.14
   293.3 1056.74   297.5 1054.49   300.1 1053.45   309.7 1053.18  317.521054.528
   328.9 1056.61   385.5 1057.26   420.7  1059.9   460.7 1059.61   499.4 1062.65
   541.9 1080.54   561.7 1094.23   594.2 1114.24   613.2 1117.72   619.2 1122.35
#Mann= 5, -1 ,  0
       0     0.1       0   297.5   0.045       0  317.52     0.1       0
  416.25    0.06       0  560.71     0.1       0
Bank Sta=297.5,317.52
XS Rating Curve= 0 ,0
Exp/Cntr(USF)=0,0
Exp/Cntr=0.3,0.1

Type RM Length L Ch R = 1 ,18002   ,504.2,501,492.4
XS GIS Cut Line= 6
1679442.57963093426663.6203959291679521.50598225426714.213798672
1679595.17020501426761.4345047621679805.64025651426896.350901589
1679879.30480734426943.5712795851679958.23083059426994.165010422
#Sta/Elev= 30
       0  1147.8    46.2  1143.1    82.6 1137.14   101.6 1132.85   134.9 1123.38
   218.9 1092.26   229.9 1090.04   250.8 1083.87   253.7 1082.31   277.4 1061.16
  294.921047.887   297.1 1046.92   301.2 1046.64   310.7 1046.88   314.5 1047.78
   320.4 1050.19   324.9  1050.8   362.9 1052.05   377.2 1053.83   400.9 1054.94
     410 1058.85   412.9 1059.27   434.2 1058.52   446.4 1069.84   462.7 1078.97
   476.1 1083.42   500.7 1094.48   567.2 1119.04   583.7 1124.58   612.5  1132.1
#Mann= 5, -1 ,  0
       0     0.1       0  294.92   0.045       0   314.5     0.1       0
  406.25    0.06       0  588.75     0.1       0
Bank Sta=294.92,314.5
XS Rating Curve= 0 ,0
Exp/Cntr(USF)=0,0
Exp/Cntr=0.3,0.1

Type RM Length L Ch R = 1 ,17501   ,500.3,500.6,500.4
XS GIS Cut Line= 6
1679180.04669142427254.7661952531679361.22119784427259.992890835
  1679436.190208427262.1552880851679611.11735159427267.201537833
1679698.58108743427269.724498674  1679792.429653427269.913474679
#Sta/Elev= 30
       0 1219.58    36.1 1200.43    56.1 1191.58    68.1 1184.58    80.1 1180.84
    96.1 1170.49   128.1 1152.25   144.1  1147.9   163.1 1138.76   200.2 1113.34
   220.2 1102.47   244.2 1086.13   260.2 1077.02   264.2 1072.91   272.2 1066.63
   280.2 1057.26  298.391044.709   300.2 1043.57   308.2 1043.04   320.2 1044.48
   336.2 1045.72   356.3 1049.28   416.2 1050.41   444.3 1049.78   468.3 1051.56
   484.1  1054.8   508.3 1054.09   520.3 1062.13   544.3 1076.39   612.6 1105.36
#Mann= 5, -1 ,  0
       0     0.1       0  286.25    0.06       0  298.39   0.045       0
   320.2    0.06       0  578.75     0.1       0
Bank Sta=298.39,320.2
XS Rating Curve= 0 ,0
Exp/Cntr(USF)=0,0
Exp/Cntr=0.3,0.1

Type RM Length L Ch R = 1 ,17000   ,502.9,499.9,496.4
XS GIS Cut Line= 6
1679193.50466976427713.8440172521679287.96182993427732.651066259
1679376.27562967427749.1444715861679451.97921842427760.372467503
1679551.93800801427763.9393895121679808.26951633427756.257646337
#Sta/Elev= 30
       0 1090.59    27.1 1087.74    92.4 1077.43   116.8 1071.91     129 1067.19
   133.1 1066.36   153.4 1065.28   181.7 1058.29   198.1 1047.84   206.2 1044.93
   250.7 1043.25   290.8 1043.58   294.8  1042.8  300.871040.227   314.9 1039.38
   322.9 1040.17   332.5 1045.09   342.9  1048.8   354.9 1049.02   370.9 1048.04
   378.9 1053.14   386.9 1060.48   410.9 1076.22   428.3 1085.73   450.9 1096.13
   470.9 1106.35   498.9 1117.51     545 1138.04     579 1149.09   619.2 1158.15
#Mann= 5, -1 ,  0
       0     0.1       0  272.68    0.06       0  300.87   0.045       0
   322.9    0.06       0  372.71     0.1       0
Bank Sta=300.87,322.9
XS Rating Curve= 0 ,0
Exp/Cntr(USF)=0,0
Exp/Cntr=0.3,0.1

Type RM Length L Ch R = 1 ,16500   ,268.2,263.5,258.3
XS GIS Cut Line= 6
1679199.27467135428311.5977430051679376.47313584428273.490535751
1679449.79680809428257.7218665031679620.88537668428220.928961083
1679706.42949693428202.5320162621679798.08416925428182.821753845
#Sta/Elev= 30
       0 1168.22      50    1155    78.6  1145.1      95  1140.8   131.8 1128.05
   158.7 1117.66   209.5 1096.03   242.3 1079.21   262.6 1060.26   266.8 1052.52
   270.9 1046.99   279.4 1040.35   289.5 1037.15   299.4 1036.09   316.4 1037.04
   328.2 1039.31   360.9 1039.46   385.5 1042.08   401.8 1041.58   417.5 1044.24
   434.6 1049.04   459.1 1063.01   471.4 1074.08   474.7 1076.23   492.3 1079.59
   516.4 1096.42   524.6  1099.9   557.3 1116.98   575.7 1123.99   612.5 1135.46
#Mann= 5, -1 ,  0
       0     0.1       0  276.25    0.06       0   289.5   0.045       0
   316.4    0.06       0  471.25     0.1       0
Bank Sta=289.5,316.4
XS Rating Curve= 0 ,0
Exp/Cntr(USF)=0,0
Exp/Cntr=0.3,0.1

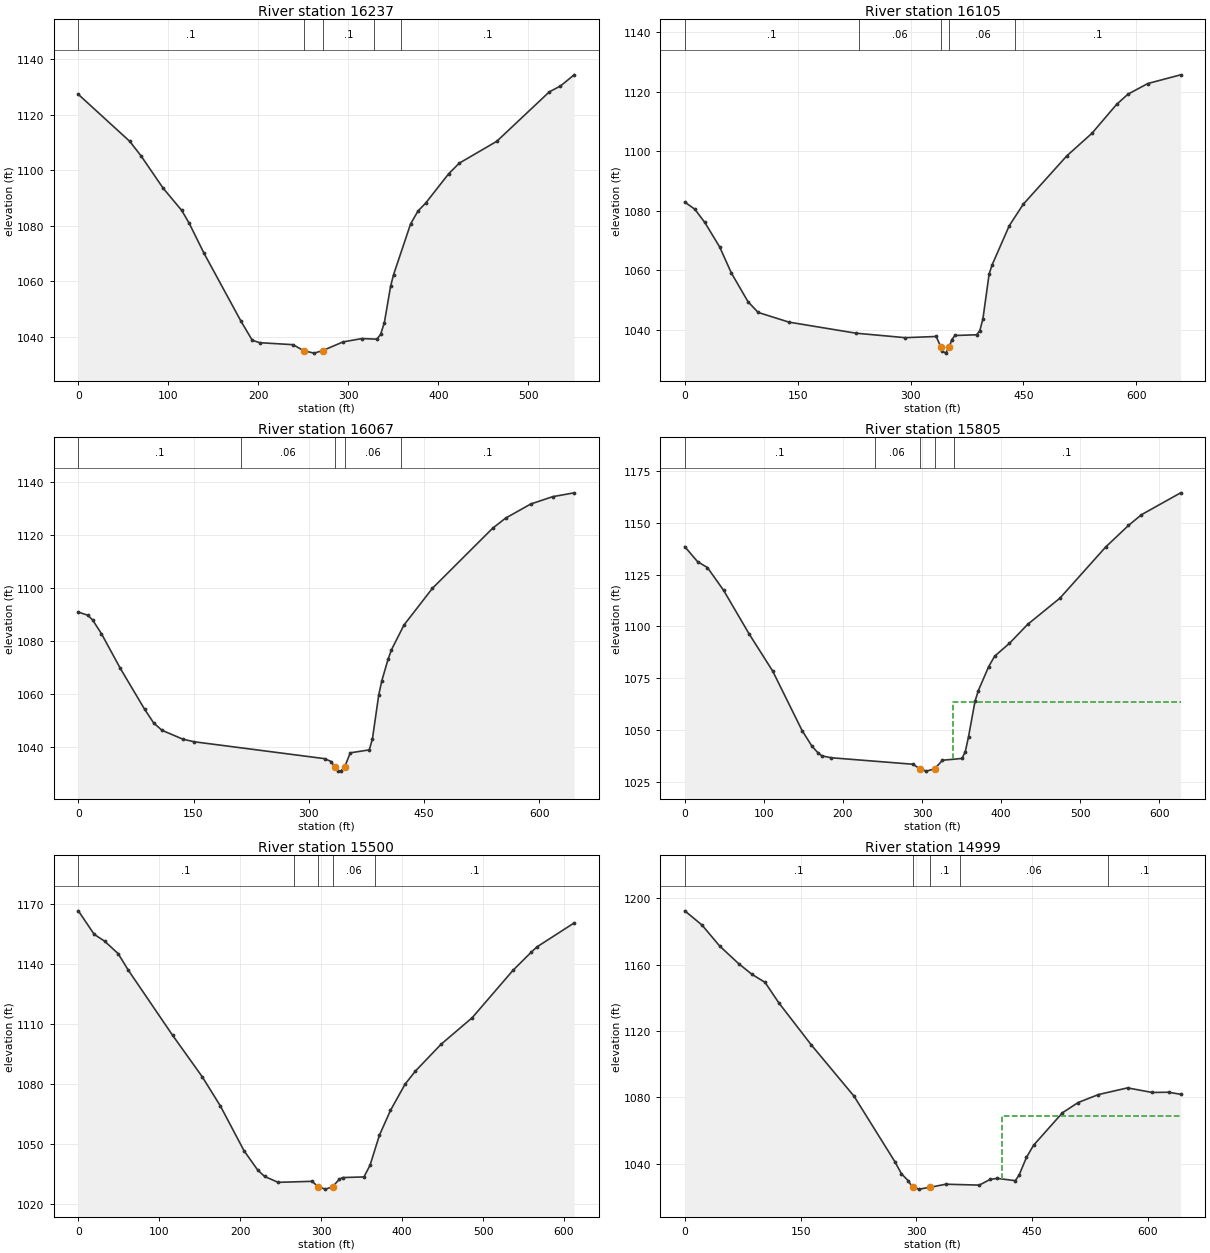
Type RM Length L Ch R = 1 ,16237   ,129.6,131.3,134
BEGIN DESCRIPTION:
Structure 4 XS 4
END DESCRIPTION:
XS GIS Cut Line= 5
1679348.70080376428467.3506782761679529.58339902428512.986195429
1679583.51628293428499.7104086211679613.38680325428478.137255058
1679874.75385603428402.631217586
#Sta/Elev= 30
       0 1127.38    57.1 1110.44    69.5 1105.27    94.3  1093.5   114.9 1085.51
   123.2 1080.87   139.7 1070.03   180.9 1045.44   193.3 1038.65   201.5 1037.78
   238.6 1037.06   250.5 1034.88     262 1034.01  271.441034.915   294.3 1038.07
   315.1 1039.26   331.7 1039.05   335.9 1040.74   340.1 1045.04     347 1058.12
   350.3 1062.32   369.2  1080.6   377.5 1085.31   385.9 1088.11   411.6 1098.75
   423.3 1102.55     465 1110.44   523.3 1128.26   535.8 1130.41     551 1134.43
#Mann= 5, -1 ,  0
       0     0.1       0   250.5   0.045       0  271.44     0.1       0
  328.94    0.06       0  358.94     0.1       0
Bank Sta=250.5,271.44
XS Rating Curve= 0 ,0
Exp/Cntr(USF)=0,0
Exp/Cntr=0.3,0.1

Type RM Length L Ch R = 1 ,16105   ,38.6,38.8,38.8
BEGIN DESCRIPTION:
Structure 4 XS 3
END DESCRIPTION:
XS GIS Cut Line= 6
1679376.08211405428766.0558814591679485.60735522428714.612207578
1679567.75128609428634.9574867291679596.79206974428622.511436596
1679616.70574995 428612.554596491679974.32225709428518.794352158
#Sta/Elev= 30
       0  1082.9    13.3 1080.52    26.6 1076.06    46.3 1067.86    61.9 1059.08
      84 1049.46    97.4 1045.86   138.4 1042.59   227.4 1038.88   292.8 1037.37
   334.2 1037.77  340.03 1034.36   342.4 1032.83   346.6 1032.18   351.61034.218
   354.8 1036.71     359  1038.1   387.9 1038.34   392.1 1039.74   396.2 1043.64
   404.5 1058.77   408.6 1061.91   431.3    1075   449.9  1082.2   507.8 1098.44
   541.1    1106   573.8 1115.68     589 1119.14   615.4 1122.72     659 1125.64
#Mann= 5, -1 ,  0
       0     0.1       0  231.01    0.06       0  340.03   0.045       0
   351.6    0.06       0  439.29     0.1       0
Bank Sta=340.03,351.6
XS Rating Curve= 0 ,0
Exp/Cntr(USF)=0,0
Exp/Cntr=0.3,0.1

Type RM Length L Ch R = 1 ,16067   ,261.3,261.1,260.5
BEGIN DESCRIPTION:
Structure 4 XS 2
END DESCRIPTION:
XS GIS Cut Line= 6
1679387.69842751428792.607455075 1679499.7128787428733.696151114
1679553.64576261428680.5930038821679599.28127976428654.871166941
1679653.21416367428642.4251168081679979.30067715428562.770395959
#Sta/Elev= 30
       0 1090.91    12.2 1089.74    18.5 1087.99      30 1082.82    54.7 1069.71
    86.3 1054.33    98.1 1049.18   108.9 1046.41   136.2 1043.05     151 1042.08
   320.6 1035.73   329.4 1034.64   333.8 1032.48   337.7 1031.08   341.8 1031.03
  346.661032.458   354.1 1037.92   378.9 1039.03     383 1043.19   391.2 1059.69
   395.3 1065.15   403.3 1073.07   407.7 1076.68   424.1 1086.05   461.2 1099.89
   539.4 1122.44   556.5  1126.3   589.2  1131.6   617.7 1134.36   645.7 1135.81
#Mann= 5, -1 ,  0
       0     0.1       0  212.25    0.06       0   333.8   0.045       0
  346.66    0.06       0  419.99     0.1       0
Bank Sta=333.8,346.66
XS Rating Curve= 0 ,0
Exp/Cntr(USF)=0,0
Exp/Cntr=0.3,0.1

Type RM Length L Ch R = 1 ,15805   ,305.9,305.4,304.7
BEGIN DESCRIPTION:
Structure 4 XS 1
END DESCRIPTION:
XS GIS Cut Line= 2
1679428.39785731428967.9252936241680036.02034366428813.336178468
#Sta/Elev= 30
       0 1138.46    16.2 1131.21    28.6  1128.4    49.2 1117.31    81.5 1096.26
   111.1 1078.46   148.3 1049.74   160.7 1042.25   168.9 1038.78   173.7 1037.48
   185.4  1036.6   288.6 1033.47   296.9 1031.34   305.3 1030.15     316 1031.23
   325.8  1035.4   350.5 1036.26   354.7 1039.55   358.8  1046.8     367 1063.86
   371.2 1069.03   384.2 1080.53   391.8 1085.61   410.6 1091.85   433.6 1100.98
   474.4 1113.63   532.3 1138.33     561 1148.68   577.5 1153.89     627 1164.44
#Mann= 5, -1 ,  0
       0     0.1       0     240    0.06       0   296.9   0.045       0
     316    0.06       0     340     0.1       0
#XS Ineff= 2 , 0
                          339.68         1063.59
Permanent Ineff=
       F       F
Bank Sta=296.9,316
XS Rating Curve= 0 ,0
Exp/Cntr(USF)=0,0
Exp/Cntr=0.3,0.1

Type RM Length L Ch R = 1 ,15500   ,503,500.7,495.5
XS GIS Cut Line= 6
 1679509.4659801429282.700459585 1679681.8022496 429226.56015192
1679753.11378676429203.3292272541679848.19594568429172.355535924
1679919.50748284429149.1246112591680091.84375234  429092.9839755
#Sta/Elev= 30
       0 1166.48    19.6 1154.73    32.4 1151.34    49.1 1145.12    61.7 1136.83
   116.4 1104.29     153 1083.56   175.5 1068.91   204.7 1046.53   221.5 1036.94
     230 1033.72   246.8 1030.74   288.9 1031.26  296.041028.542   305.3 1027.35
   314.1 1028.53   322.5 1032.36   326.7 1033.14   352.9 1033.45   360.4 1039.37
   371.9 1054.25   385.6 1066.73   403.6 1079.79   416.3 1086.33   448.1 1099.78
   486.6 1113.07   536.9 1136.72   559.1 1145.65   566.5 1148.44   612.5 1160.43
#Mann= 5, -1 ,  0
       0     0.1       0  266.25    0.06       0  296.04   0.045       0
   314.1    0.06       0  366.25     0.1       0
Bank Sta=296.04,314.1
XS Rating Curve= 0 ,0
Exp/Cntr(USF)=0,0
Exp/Cntr=0.3,0.1

Type RM Length L Ch R = 1 ,14999   ,488.8,497.8,510.3
XS GIS Cut Line= 6
1679667.09033675429842.5379225911679876.75231901429695.208820924
1679958.57203725429637.7148414251680029.83337767429594.200820833
1680114.30729009429543.0332722511680202.49740243429488.257791251
#Sta/Elev= 30
       0 1192.39    22.3 1183.82    45.2 1171.19    69.7 1160.61      87 1154.15
   103.9 1149.35   121.8    1137   163.5 1111.88   219.2 1080.81   272.1 1041.39
   280.7 1034.02   289.3 1029.98     295 1025.94   303.6 1024.83     318 1025.96
   338.1 1027.79   381.5 1027.25   395.6 1030.68   404.6 1031.31   428.1 1029.93
     433 1033.23   442.6 1043.96   451.8 1051.25   489.2  1070.8   509.6 1076.98
   535.9 1081.78   573.6 1085.79   605.5 1083.02   626.6 1083.18   642.3 1081.92
#Mann= 5, -1 ,  0
       0     0.1       0     295   0.045       0     318     0.1       0
  356.25    0.06       0  548.51     0.1       0
#XS Ineff= 2 , 0
                          411.14         1068.72
Permanent Ineff=
       F       F
Bank Sta=295,318
XS Rating Curve= 0 ,0
Exp/Cntr(USF)=0,0
Exp/Cntr=0.3,0.1

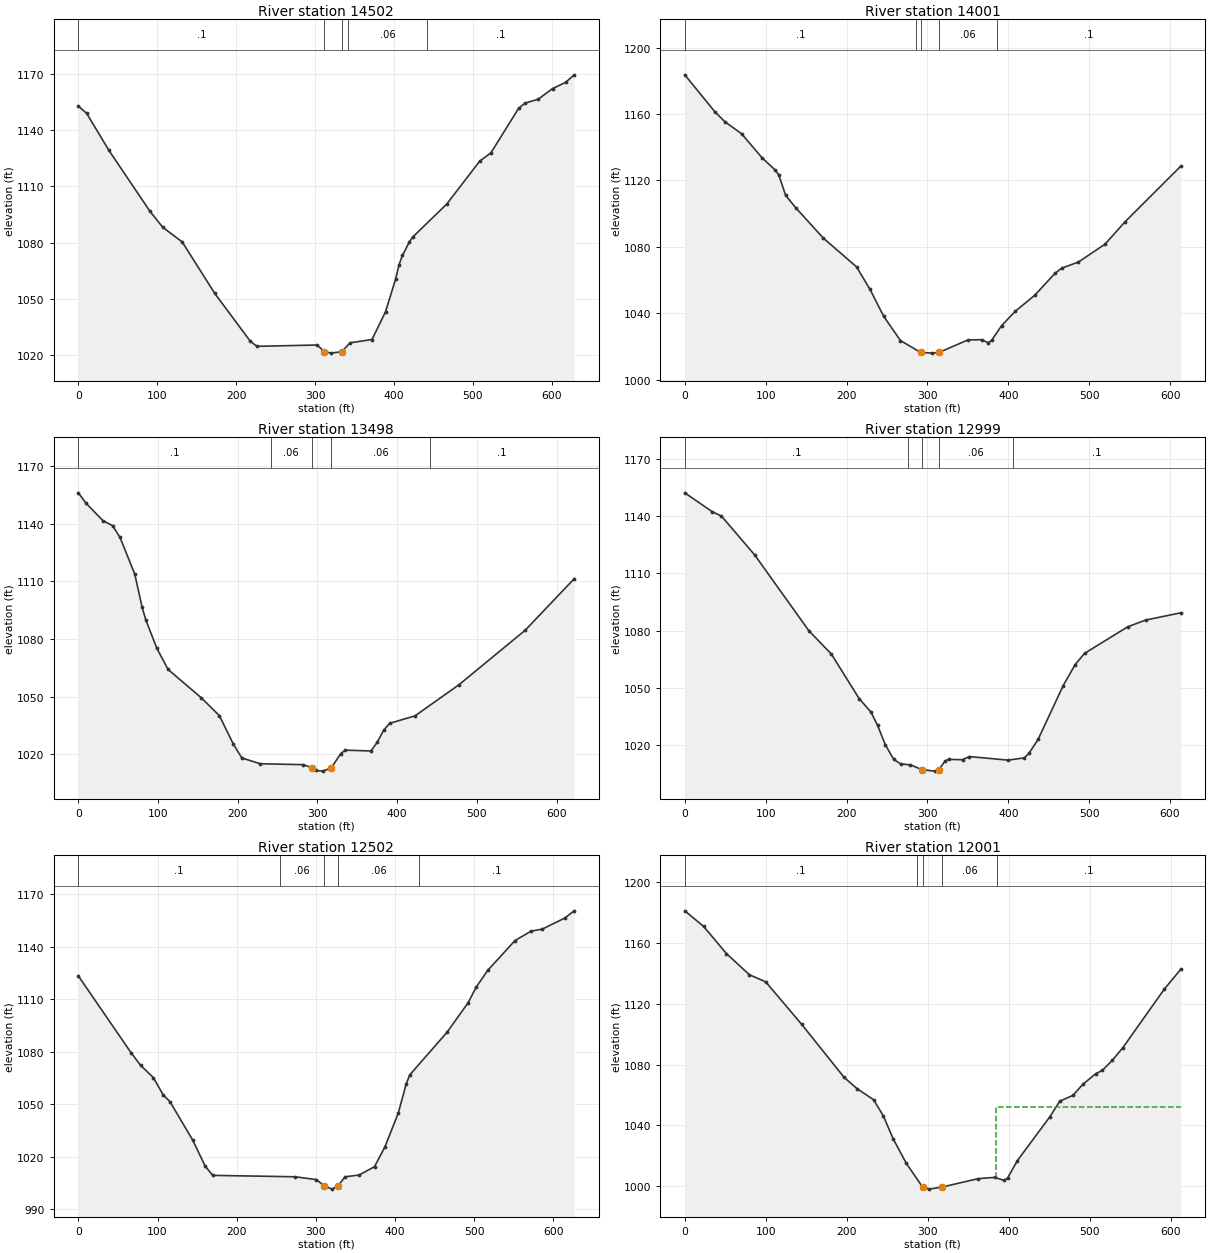
Type RM Length L Ch R = 1 ,14502   ,500.5,500.2,498.4
XS GIS Cut Line= 6
1679825.67663376430014.4660564211679932.82799426430003.132089585
1680020.12243909430021.8433382511680091.37459317430045.656938925
1680184.22250459430082.7953160851680422.14492901430177.963104755
#Sta/Elev= 30
       0 1152.92    10.5 1149.13    38.7 1129.32    90.9 1096.66     107 1088.19
   131.6 1080.41   172.7 1052.99   218.1 1027.23   226.5  1024.6   302.6 1025.29
   311.9  1021.8   320.3 1020.96   333.8 1021.74   344.5 1026.48   372.2 1028.24
   389.3 1043.03   402.2 1060.62   406.5 1068.29   410.8 1073.13   419.4 1080.32
   423.7 1082.96   466.8 1100.56   508.8 1123.59   522.8 1127.91     558 1151.75
   565.9  1154.5   582.7  1156.6   601.1 1162.34   617.6 1165.62   628.4 1169.66
#Mann= 5, -1 ,  0
       0     0.1       0   311.9   0.045       0   333.8     0.1       0
  342.15    0.06       0  442.15     0.1       0
Bank Sta=311.9,333.8
XS Rating Curve= 0 ,0
Exp/Cntr(USF)=0,0
Exp/Cntr=0.3,0.1

Type RM Length L Ch R = 1 ,14001   ,518.3,502.9,486.8
XS GIS Cut Line= 6
  1679684.736955430446.8296930041679930.18003367   430520.463404
1680025.96265051430549.1979265961680098.31388375 430569.03482917
1680183.56666601430589.3684499261680275.26989467430609.949773595
#Sta/Elev= 30
       0 1183.58    36.9 1161.49    49.5 1155.37    70.3 1148.07    95.4  1133.7
   112.1 1126.09   116.3  1123.2   124.6 1111.07   137.2 1103.53   171.1 1085.35
   212.3 1067.98     229  1054.4   245.7 1038.36   266.6 1023.61   291.7 1016.46
     306 1016.06  314.241016.471   350.1 1024.03   366.8 1024.12   375.1 1022.32
   379.2 1023.69   391.7 1032.66   408.3 1041.18   432.4  1050.8   457.8 1064.17
     466 1067.22   486.6  1070.9   519.5 1081.67   544.1 1095.06   612.9 1128.52
#Mann= 5, -1 ,  0
       0     0.1       0  286.25    0.06       0   291.7   0.045       0
  314.24    0.06       0  386.25     0.1       0
Bank Sta=291.7,314.24
XS Rating Curve= 0 ,0
Exp/Cntr(USF)=0,0
Exp/Cntr=0.3,0.1

Type RM Length L Ch R = 1 ,13498   ,495.1,499.1,502.7
XS GIS Cut Line= 6
1679931.21284001431245.6998144241680060.32872351 431024.35544084
1680110.71576184430937.9776608351680147.93845643430872.863289759
1680201.40586917430801.2541810131680281.19048651430738.660146087
#Sta/Elev= 30
       0 1156.08     9.7 1150.65    30.8 1141.63      43 1138.99    52.3 1132.89
    70.8 1113.79    80.1 1096.45    84.7 1089.89    98.6 1075.14   112.6  1064.2
   154.2 1049.48     177 1040.15   194.5 1025.33   205.1 1018.17   228.3 1015.15
   282.3 1014.68   293.1 1013.11   297.7 1011.66     307 1011.32   317.4 1013.03
   329.1 1020.41   334.9 1022.22   367.1 1021.81   375.2 1026.48   383.2 1032.73
   390.6 1036.18   422.4 1040.08   477.3 1056.19   560.7 1084.65     622 1111.38
#Mann= 5, -1 ,  0
       0     0.1       0  241.25    0.06       0   293.1   0.045       0
   317.4    0.06       0  441.25     0.1       0
Bank Sta=293.1,317.4
XS Rating Curve= 0 ,0
Exp/Cntr(USF)=0,0
Exp/Cntr=0.3,0.1

Type RM Length L Ch R = 1 ,12999   ,484.7,497.4,509.7
XS GIS Cut Line= 6
1680236.02751909431488.2977544221680432.03532918431323.237060919
  1680508.262867431258.510484338 1680563.2411035431207.361964583
1680627.53001693431147.679341167 1680697.3274495431084.601383343
#Sta/Elev= 30
       0 1152.23      34 1142.32    45.3 1140.08    86.6 1119.62   153.2 1080.15
   181.3 1067.77   215.6  1044.5   230.2 1037.45   238.4 1030.46     248  1020.3
   258.2  1012.8   266.8  1010.3     279 1009.81   293.1 1007.35   308.8 1006.53
   314.1 1007.33   322.2 1011.99   326.3 1012.68   343.4 1012.51   351.9 1014.15
   399.8 1012.28   419.8 1013.48   425.5 1015.84   436.8 1023.09   467.9 1051.32
   482.5 1062.19   494.3 1068.18   547.6 1082.08   569.8 1085.61   613.1  1089.4
#Mann= 5, -1 ,  0
       0     0.1       0  276.25    0.06       0   293.1   0.045       0
   314.1    0.06       0  406.25     0.1       0
Bank Sta=293.1,314.1
XS Rating Curve= 0 ,0
Exp/Cntr(USF)=0,0
Exp/Cntr=0.3,0.1

Type RM Length L Ch R = 1 ,12502   ,505.5,500.9,494.8
XS GIS Cut Line= 6
  1680290.826294431630.7587555941680391.42058101431649.714754418
1680480.19960292431675.2461994291680543.00557968431716.349463671
1680756.60882701431868.9272425031680832.89607601431923.418603346
#Sta/Elev= 30
       0 1123.27    66.4 1079.52    78.6  1072.2    94.9 1065.12   107.2  1055.3
   115.6 1051.55   144.7 1029.29   160.2 1014.59   169.7 1009.38   273.6 1008.57
   300.7 1006.95  310.141003.473   320.3 1001.52   328.1 1003.44   336.7 1008.54
   354.7 1009.58     374 1014.35   387.1 1025.58   403.9  1044.8   414.1 1061.71
   418.6 1066.78   465.7 1091.16   492.4 1108.03   502.2 1116.74   517.3  1126.6
   551.4 1143.44   571.8 1148.85   585.8 1149.97   614.2 1156.28   626.1 1160.42
#Mann= 5, -1 ,  0
       0     0.1       0  254.74    0.06       0  310.14   0.045       0
   328.1    0.06       0   429.8     0.1       0
Bank Sta=310.14,328.1
XS Rating Curve= 0 ,0
Exp/Cntr(USF)=0,0
Exp/Cntr=0.3,0.1

Type RM Length L Ch R = 1 ,12001   ,435.4,437.2,439.1
XS GIS Cut Line= 6
1680069.09314168432150.1100790951680161.97747034432162.820355505
1680248.66955417 432174.683192671680422.05372185432198.409195095
1680496.36131601432208.5771537571680675.93772851432233.150923505
#Sta/Elev= 30
       0 1181.15    23.2 1170.92    51.5    1153    79.8  1139.1    99.9 1134.46
   144.4 1106.46   196.8  1071.6     213 1064.08   233.2 1056.91   245.3  1046.2
   257.4  1031.2   273.5 1015.17   293.7  999.43   301.8  998.08     318  999.47
   362.4 1004.97   382.6  1005.8   394.7 1003.83   398.7 1005.38   410.8 1016.81
   451.2 1045.84   463.3 1055.99   479.4 1059.73   491.6 1066.96   507.7 1074.03
   515.8 1076.17   527.9  1082.7   541.1  1091.1   592.5 1129.77   612.5 1142.56
#Mann= 5, -1 ,  0
       0     0.1       0  286.25    0.06       0   293.7   0.045       0
     318    0.06       0  386.25     0.1       0
#XS Ineff= 2 , 0
                          384.47         1052.16
Permanent Ineff=
       F       F
Bank Sta=293.7,318
XS Rating Curve= 0 ,0
Exp/Cntr(USF)=0,0
Exp/Cntr=0.3,0.1

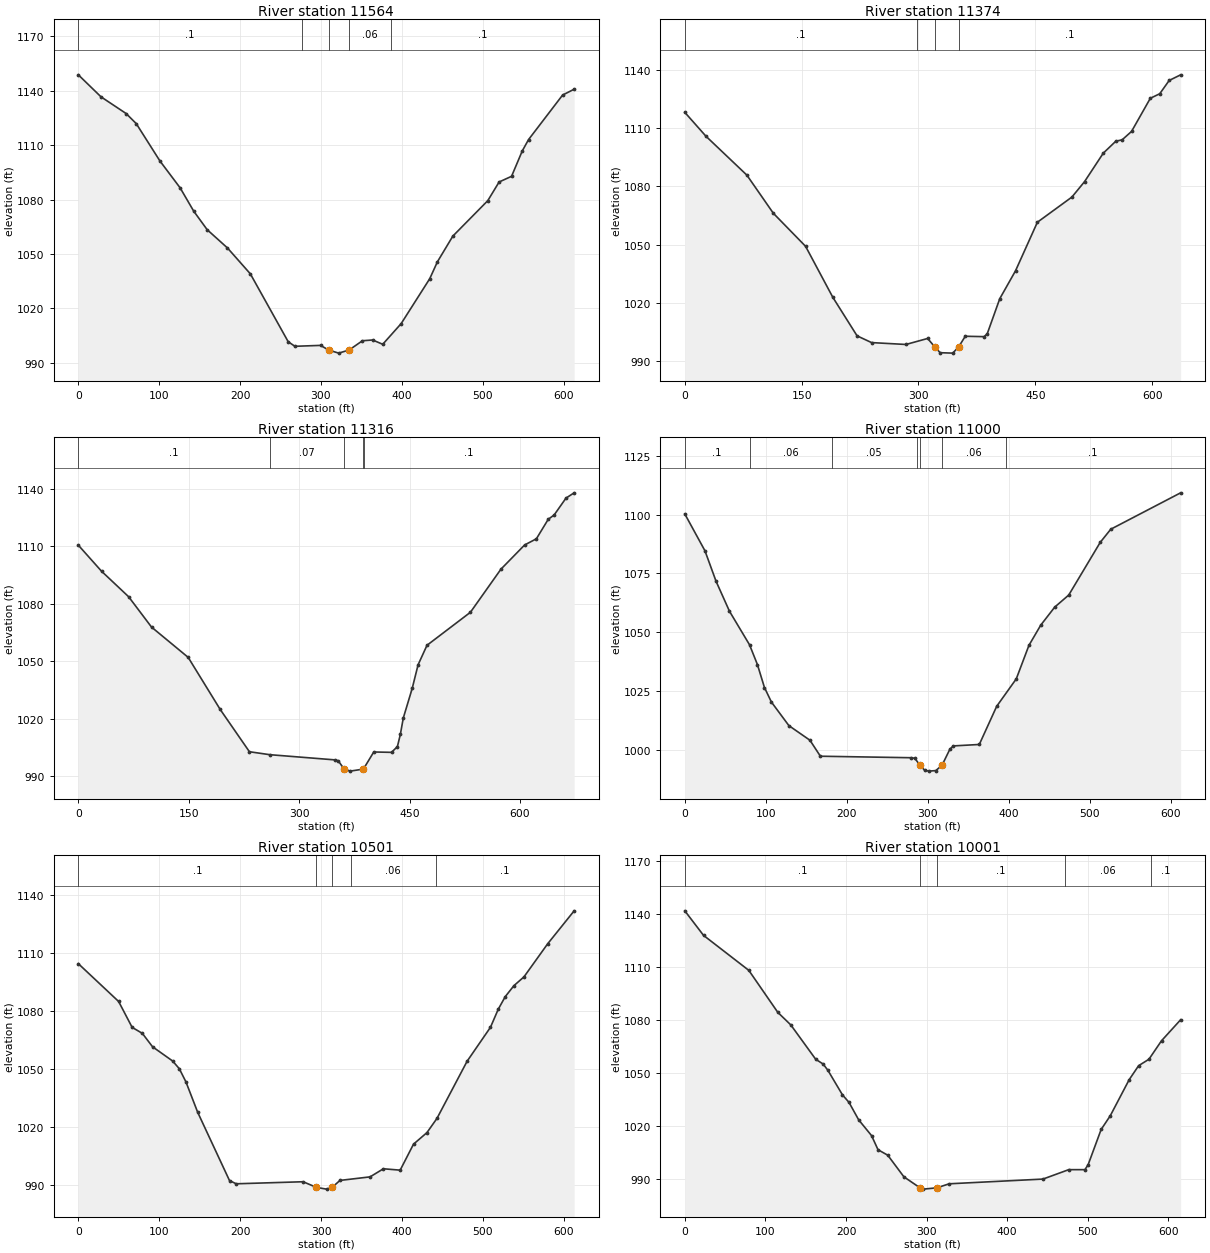
Type RM Length L Ch R = 1 ,11564   ,192.6,190.2,187.5
BEGIN DESCRIPTION:
Structure 3 XS 4
END DESCRIPTION:
XS GIS Cut Line= 6
1679983.45900198432520.5249086571680157.13614807432572.369293164
1680324.82446099432622.4256234871680396.69111515432643.877352248
1680480.11483282432670.6919311541680569.78328865432699.759130235
#Sta/Elev= 30
       0 1148.82      28 1136.69    59.1 1127.46    71.6 1121.91   100.9 1101.28
   125.9 1086.44   142.6 1073.64   159.3 1063.37   184.4 1053.29   212.7    1039
   259.5 1001.54   267.8  999.02   299.5  999.52   309.6  996.92     322  995.25
   334.9  996.99   351.3 1002.08   363.9  1002.5   376.4 1000.13   399.2 1011.55
   434.5  1036.3     444 1045.63   463.1 1059.83   506.3 1079.39   520.3 1089.69
   535.7 1092.82   548.9 1106.79   556.7 1113.08   598.8 1137.65   613.1 1140.88
#Mann= 5, -1 ,  0
       0     0.1       0  276.25    0.06       0   309.6   0.045       0
   334.9    0.06       0  386.25     0.1       0
Bank Sta=309.6,334.9
XS Rating Curve= 0 ,0
Exp/Cntr(USF)=0,0
Exp/Cntr=0.3,0.1

Type RM Length L Ch R = 1 ,11374   ,57.9,57.6,57.4
BEGIN DESCRIPTION:
Structure 3 XS 3
END DESCRIPTION:
XS GIS Cut Line= 3
1679990.04602635432585.8888535811680206.30112696432790.762106793
1680542.69795013 432829.96624784
#Sta/Elev= 30
       0 1118.27    27.1 1105.96    79.7 1085.85   113.7 1066.15   155.1 1049.08
   190.1 1022.73   221.2 1002.86   239.8  999.38   283.9  998.41   311.8 1001.51
  320.89997.1692   327.9  994.16     344  993.94   351.6  997.15   360.1 1002.65
   384.3 1002.45   388.3 1003.93   404.4 1022.05   424.6 1036.43   452.7 1061.53
     497 1074.52   513.2 1082.46   537.3  1097.2   553.4 1103.37   561.5 1104.07
   573.6 1108.42   597.7 1125.53   609.8 1127.87   621.9 1134.73   636.6 1137.64
#Mann= 4, -1 ,  0
       0     0.1       0  297.89    0.07       0  320.89   0.045       0
   351.6     0.1       0
Bank Sta=320.89,351.6
XS Rating Curve= 0 ,0
Exp/Cntr(USF)=0,0
Exp/Cntr=0.3,0.1

Type RM Length L Ch R = 1 ,11316   ,322.6,316.2,309.6
BEGIN DESCRIPTION:
Structure 3 XS 2
END DESCRIPTION:
XS GIS Cut Line= 3
1679967.28233154432604.8585992491680201.24252811432848.935993508
1680535.11005187432880.552236287
#Sta/Elev= 30
       0 1110.68    31.5 1097.09    68.3 1083.76    99.4 1067.91   149.2 1052.08
   192.7 1024.88   232.4 1002.79     260 1001.25     349  998.52     353  998.08
   361.1  993.72   369.1  992.66   386.8993.6885   388.1  994.28   401.3 1002.66
   425.4 1002.47   433.4 1005.47   437.4 1011.81   441.4 1020.38   453.5 1035.85
   461.5  1048.2   473.6 1058.39   532.6 1075.64     574 1098.13   606.2 1110.79
   622.2 1114.02   638.3 1124.21   646.3 1126.45   662.4 1135.27   673.5 1138.03
#Mann= 5, -1 ,  0
       0     0.1       0     260    0.07       0   361.1   0.045       0
   386.8    0.07       0   388.1     0.1       0
Bank Sta=361.1,386.8
XS Rating Curve= 0 ,0
Exp/Cntr(USF)=0,0
Exp/Cntr=0.3,0.1

Type RM Length L Ch R = 1 ,11000   ,490.6,498.6,505.4
BEGIN DESCRIPTION:
Structure 3 XS 1
END DESCRIPTION:
XS GIS Cut Line= 6
1679985.03589509433275.8197699191680071.82049842433240.359210923
1680314.81837201433141.0700394211680384.24638276433112.701329753
1680465.24589267433079.6059235041680551.81724185433043.623055846
#Sta/Elev= 30
       0 1100.28    24.9 1084.62    38.6 1071.69    55.2 1058.94      80 1044.68
    89.7 1036.31    98.4 1026.55     107 1020.38   128.6 1010.36   154.6 1004.16
   167.5  997.37   279.9  996.73   284.2  996.48   290.2  993.68   296.3   991.4
   301.5  991.04   310.1  991.27   317.8  993.56   327.4 1000.31   331.7 1001.75
   363.8 1002.36   385.3 1018.58   409.5 1030.24   425.1 1044.44   439.7 1053.04
     457 1060.71   474.3 1065.83   513.2 1088.21   526.2 1093.78   612.5 1109.24
#Mann= 7, -1 ,  0
       0     0.1       0      80    0.06       0  181.25    0.05       0
  286.25    0.06       0   290.2   0.045       0   317.8    0.06       0
  396.25     0.1       0
Bank Sta=290.2,317.8
XS Rating Curve= 0 ,0
Exp/Cntr(USF)=0,0
Exp/Cntr=0.3,0.1

Type RM Length L Ch R = 1 ,10501   ,502.7,500.4,498.4
XS GIS Cut Line= 6
1680028.58633292433557.0816745911680118.27086484433584.989099085
1680275.46871318433626.1606046711680372.20605251 433651.49684009
  1680444.759057433670.4987705951680620.09499243  433716.4196105
#Sta/Elev= 30
       0 1104.51    49.8 1084.95    66.5 1071.56    79.1 1068.46    91.7 1061.53
   116.5 1054.17   124.8 1050.16     133 1043.33   147.5 1027.62   186.8  992.31
   195.1  990.64   277.8   991.7   294.3  988.76   306.7  987.88   313.5988.7543
   323.3  992.38   360.5  994.22     377  998.41   397.7  997.69   414.2 1011.15
   430.8 1017.12   443.2 1024.49   480.4 1054.03   509.3 1071.61   518.9 1080.95
   527.6 1087.49   538.3 1093.15   550.7 1097.69     580 1114.81   612.7 1131.85
#Mann= 5, -1 ,  0
       0     0.1       0   294.3   0.045       0   313.5     0.1       0
  336.43    0.06       0  441.43     0.1       0
Bank Sta=294.3,313.5
XS Rating Curve= 0 ,0
Exp/Cntr(USF)=0,0
Exp/Cntr=0.3,0.1

Type RM Length L Ch R = 1 ,10001   ,492.4,499,503.5
XS GIS Cut Line= 6
1679776.95429026434034.3320324271679957.75970292434047.020327255
1680132.33021992434059.2706308361680207.14634326434064.520620346
1680294.40830784434070.9792688341680386.53476401434099.237086341
#Sta/Elev= 30
       0 1141.62    23.2 1127.79    79.4 1108.03   115.4 1084.31   131.5 1077.23
   162.4 1057.84   171.6 1055.16   177.4  1051.7   195.6 1037.75   203.7 1033.51
   215.7 1023.66   231.7 1014.74   239.7 1006.79   251.8 1003.69   271.8  991.49
   291.9  985.26   295.9  984.55  312.67985.2778     328  987.56   444.3  990.22
   476.3  995.54   496.4  995.54   500.4  998.37   516.5 1018.22   527.8 1025.95
   551.3 1046.34     563 1054.22   575.8 1057.86   591.4 1068.29   615.1 1080.14
#Mann= 5, -1 ,  0
       0     0.1       0   291.9   0.045       0  312.67     0.1       0
  471.25    0.06       0  578.75     0.1       0
Bank Sta=291.9,312.67
XS Rating Curve= 0 ,0
Exp/Cntr(USF)=0,0
Exp/Cntr=0.3,0.1