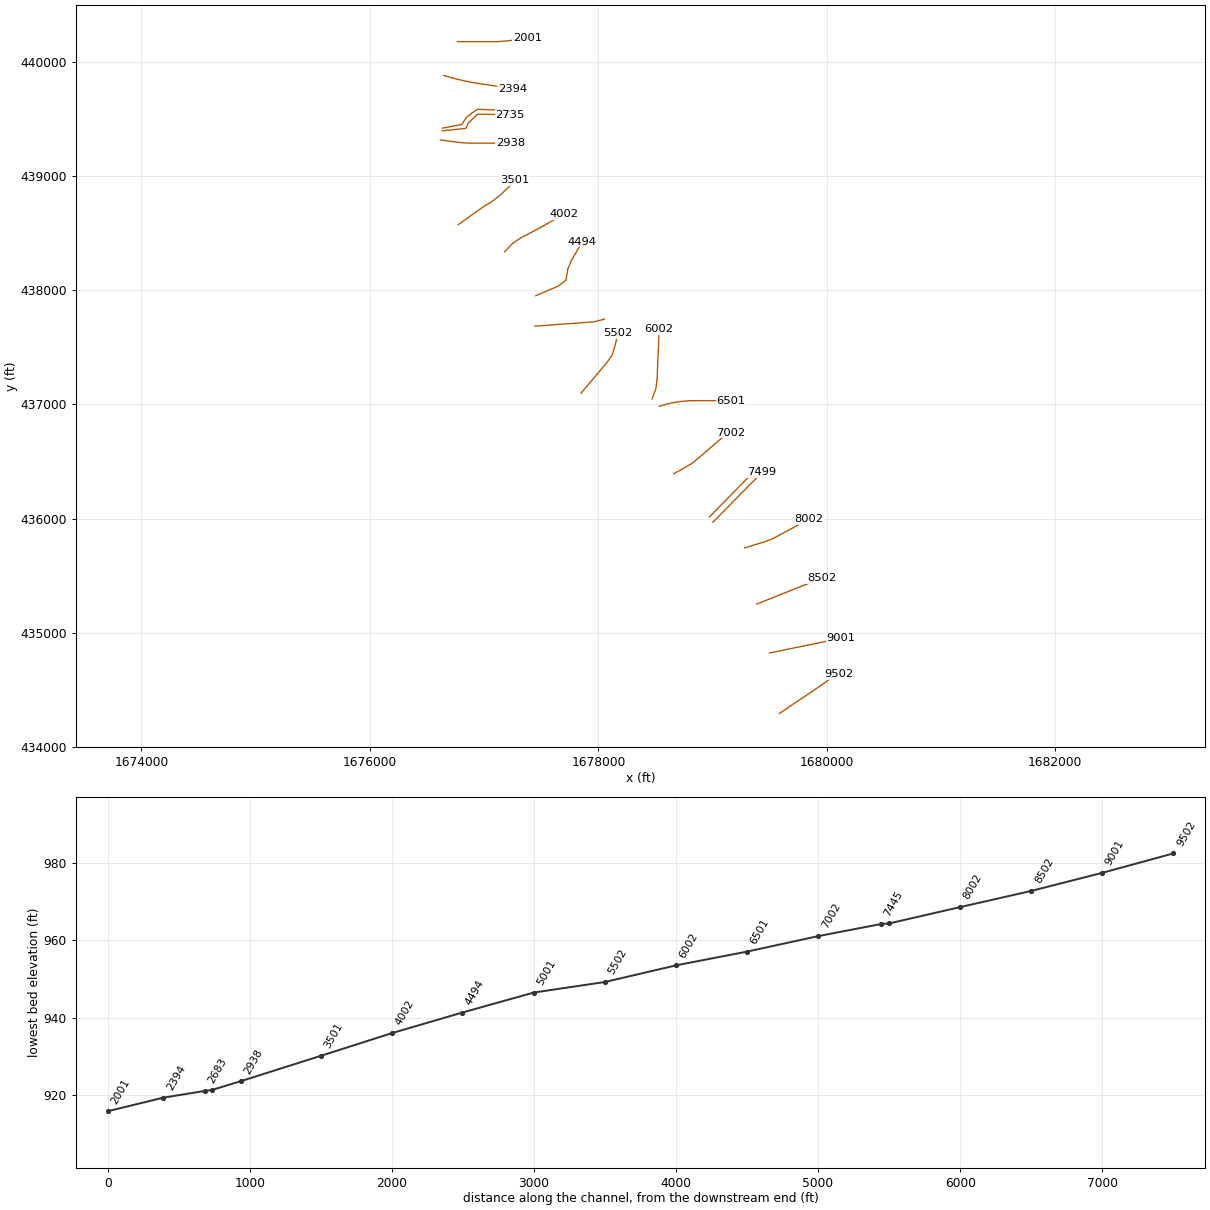
HEC-RAS study SUGARRN.prj: SUGARRN

--- SUGARRN.g01 (geometry) --- (continued)

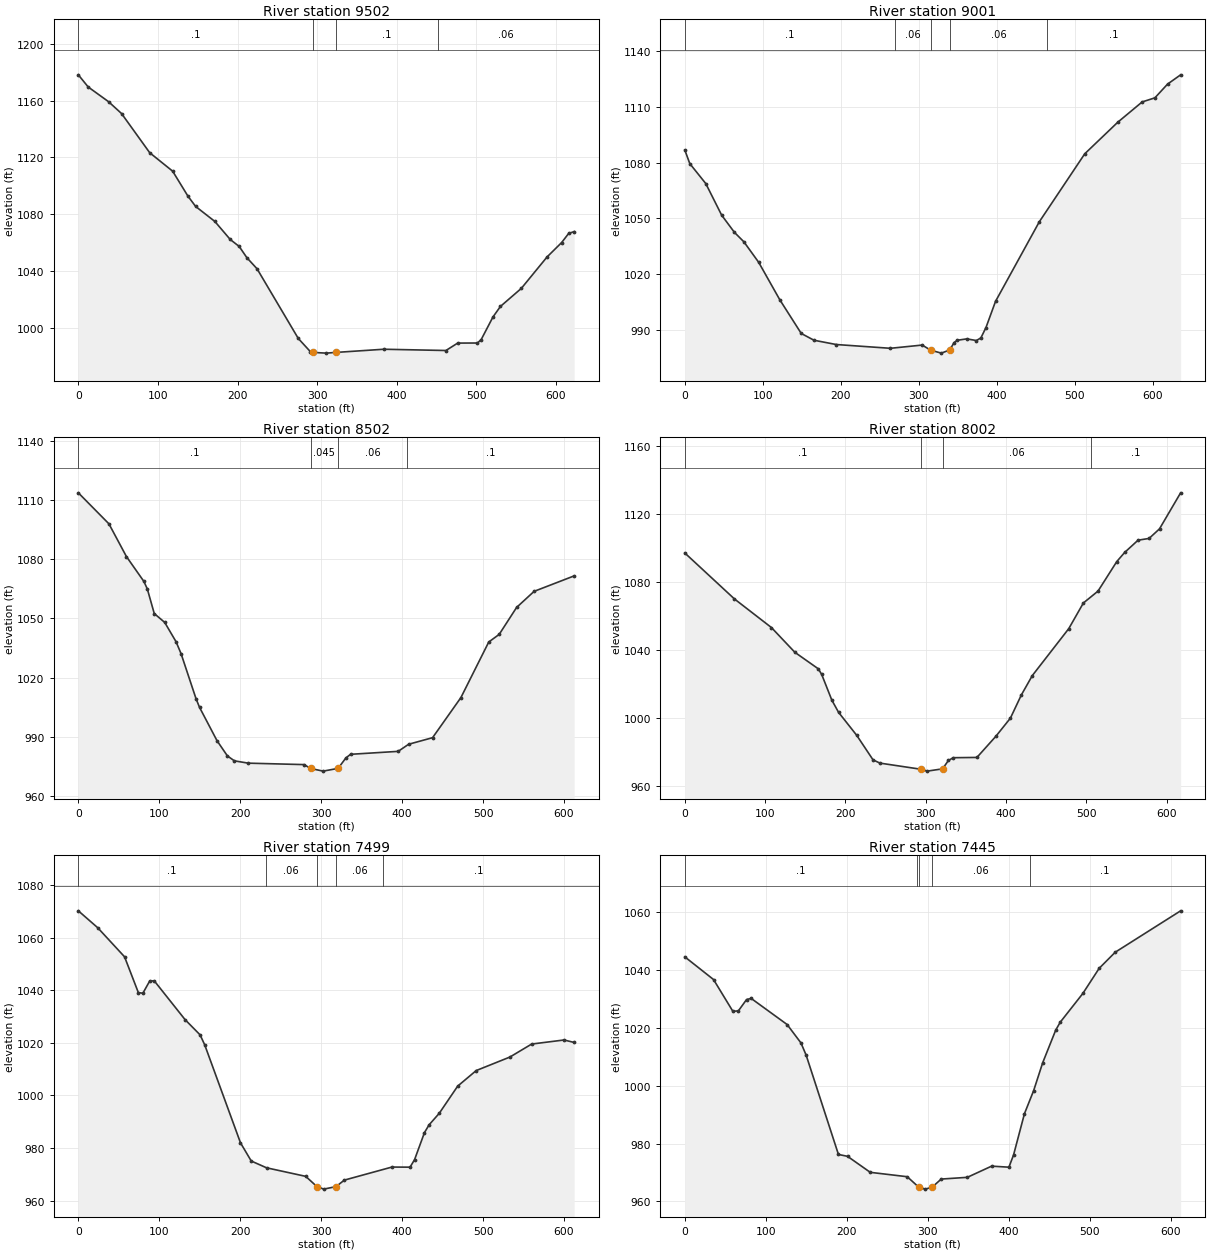
Type RM Length L Ch R = 1 ,9502    ,502.9,501.1,489.9
XS GIS Cut Line= 6
1679585.86641784434294.2137304991679736.20207517434395.459919095
1679881.35368776434493.2149729281679943.49988893434535.622696504
1680016.35735476434587.9598621731680106.13014109434635.775711417
#Sta/Elev= 30
       0 1178.06    12.4 1169.51    37.9 1159.21    54.3 1150.85    89.7  1123.3
   118.5 1110.35   137.7  1092.8   147.4 1085.56   171.5 1075.03   190.8 1062.37
   202.1 1057.45   211.8  1049.5   224.5 1041.78   276.3  992.81   291.5  983.52
   294.4     983   311.4  982.49   323.2  982.97   383.7  985.22   461.8  984.33
   476.6  989.55   501.4   989.6   506.1  992.01   520.9  1007.9   530.3 1015.31
   556.5 1027.97   588.9  1050.1   607.2 1060.21     616  1066.6   622.9 1067.89
#Mann= 4, -1 ,  0
       0     0.1       0   294.4   0.045       0   323.2     0.1       0
  451.49    0.06       0
Bank Sta=294.4,323.2
XS Rating Curve= 0 ,0
Exp/Cntr(USF)=0,0
Exp/Cntr=0.3,0.1

Type RM Length L Ch R = 1 ,9001    ,496.8,499.3,501.7
XS GIS Cut Line= 5
1679497.80493392434823.139195802 1679869.6562046434898.875250846
1679943.03630717 434914.378500671680028.64702834434932.464750588
1680120.45786834434951.437153593
#Sta/Elev= 30
       0 1086.81     6.4 1079.48    26.9 1068.73    47.3 1051.69    63.6 1042.48
    75.8 1037.36    94.7 1026.36   121.8 1006.18   149.3  988.05   165.6   984.4
   194.2  982.09   263.6  980.06   304.4   981.8315.1154979.0608   328.9  977.46
339.6154 979.155   345.3  983.16   349.3  984.38   361.6  985.13   373.8  984.24
   379.6  985.64   386.1  991.19   398.4 1005.33   454.5 1048.14   512.8 1084.76
   555.1 1101.74   586.4 1112.67   602.7 1114.87     619 1122.28   635.7 1127.26
#Mann= 5, -1 ,  0
       0     0.1       0     270    0.06       0315.1154   0.045       0
339.6154    0.06       0  464.49     0.1       0
Bank Sta=315.1154,339.6154
XS Rating Curve= 0 ,0
Exp/Cntr(USF)=0,0
Exp/Cntr=0.3,0.1

Type RM Length L Ch R = 1 ,8502    ,497.5,499.8,499.3
XS GIS Cut Line= 6
1679384.95376192435250.9309771661679553.38912059435317.871788174
1679623.08648776435345.5721920881679785.71345909435410.204608753
1679867.02694476435442.5214732591679954.14881776 435477.14574784
#Sta/Elev= 30
       0 1113.57    37.8 1097.88    59.4 1081.34    80.9 1068.79    85.2 1064.97
    93.8 1052.49   106.7 1048.02   120.7 1038.25   126.9 1032.21   145.4 1009.41
   149.7 1005.06   171.3  988.19   184.2  980.45   192.8  977.98     210  976.81
   278.9  976.08     287  974.11   302.4  972.78   320.9  974.17   330.5  979.45
   336.3  981.29   395.1  982.78     408  986.37   437.6   989.7   472.6 1009.99
     507  1038.1   519.9 1041.96   541.4 1055.59     563 1063.72   612.5 1071.55
#Mann= 4, -1 ,  0
       0     0.1       0     287   0.045       0   320.9    0.06       0
  406.25     0.1       0
Bank Sta=287,320.9
XS Rating Curve= 0 ,0
Exp/Cntr(USF)=0,0
Exp/Cntr=0.3,0.1

Type RM Length L Ch R = 1 ,8002    ,496.6,502.2,505.1
BEGIN DESCRIPTION:
Structure 2 XS 4
END DESCRIPTION:
XS GIS Cut Line= 6
1679281.19773585435742.6652299171679373.14046533435771.743583843
 1679458.7196905435797.2218793331679529.11390667435824.683766678
1679617.16097467435872.0937768371679842.78257068435993.580082417
#Sta/Elev= 30
       0 1097.21    61.8 1070.11   107.9 1053.24   137.1 1038.64   166.3  1028.9
   170.5 1025.58   183.1 1010.47   191.5 1003.26   214.1  989.71   234.4  975.26
     243  973.33  293.88969.7188   301.8   968.6  320.98969.9374   328.3  974.87
   334.3  976.51   363.8  976.67   387.4  989.13   405.5  999.83   419.2 1013.56
   432.8 1024.93   478.2 1052.61   496.4 1067.73   514.6 1074.71     538 1092.14
   547.8 1097.51   564.5 1104.75   578.2 1105.77   591.2 1111.42   617.5 1132.66
#Mann= 4, -1 ,  0
       0     0.1       0  293.88   0.045       0  320.98    0.06       0
  506.28     0.1       0
Bank Sta=293.88,320.98
XS Rating Curve= 0 ,0
Exp/Cntr(USF)=0,0
Exp/Cntr=0.3,0.1

Type RM Length L Ch R = 1 ,7499    ,54.7,54.5,54.6
BEGIN DESCRIPTION:
Structure 2 XS 3
END DESCRIPTION:
XS GIS Cut Line= 6
1679003.30190429435968.6076914221679069.35557794436035.137742087
1679130.77146561436097.4624205831679183.31532378 436150.98003009
1679305.91809694436275.8541241741679432.89947028436405.188183084
#Sta/Elev= 30
       0 1070.28    23.9 1063.86    57.1 1052.78    74.1 1039.18    79.7  1038.9
    88.2 1043.58    93.8 1043.63   131.9 1028.85   150.4 1023.07   156.1 1019.28
   200.3  981.99   213.6  975.05   232.5  972.47   280.9  969.21   294.7  965.32
   303.2  964.35  318.35965.3125   328.6  967.78   387.4  972.75   409.8  972.71
   415.4  975.61   427.6  985.88   433.3  988.82   445.8  993.19   468.6 1003.55
   491.5 1009.48   533.1 1014.62     560 1019.57     600 1021.12   612.5 1020.18
#Mann= 5, -1 ,  0
       0     0.1       0  231.25    0.06       0   294.7   0.045       0
  318.35    0.06       0  376.25     0.1       0
Bank Sta=294.7,318.35
XS Rating Curve= 0 ,0
Exp/Cntr(USF)=0,0
Exp/Cntr=0.3,0.1

Type RM Length L Ch R = 1 ,7445    ,442.9,443,441.5
BEGIN DESCRIPTION:
Structure 2 XS 2
END DESCRIPTION:
XS GIS Cut Line= 6
1678971.13316772436013.5717741551679037.18684137 436080.10182482
1679098.60272904436142.4265033161679151.14658721436195.944112823
1679273.74936037436320.8182069071679400.73073371436450.152265817
#Sta/Elev= 30
       0 1044.57    35.5 1036.72    59.4 1025.72    66.2 1025.89    76.3  1029.8
      82 1030.19   126.4 1021.16   143.5 1014.79   149.9 1010.57   189.8  976.21
     201  975.57   229.1  970.03   274.8  968.51   289.3  964.82     297  964.22
   305.4  964.87   316.8   967.7     349   968.3     379  972.17   400.4  971.81
   406.1  976.02   419.6  990.33   430.9  998.27   442.1 1007.93   458.2 1019.23
   463.8 1021.97   491.7  1031.9   511.9 1040.61   531.7 1046.17   612.5 1060.49
#Mann= 5, -1 ,  0
       0     0.1       0  286.25    0.06       0   289.3   0.045       0
   305.4    0.06       0  426.25     0.1       0
Bank Sta=289.3,305.4
XS Rating Curve= 0 ,0
Exp/Cntr(USF)=0,0
Exp/Cntr=0.3,0.1

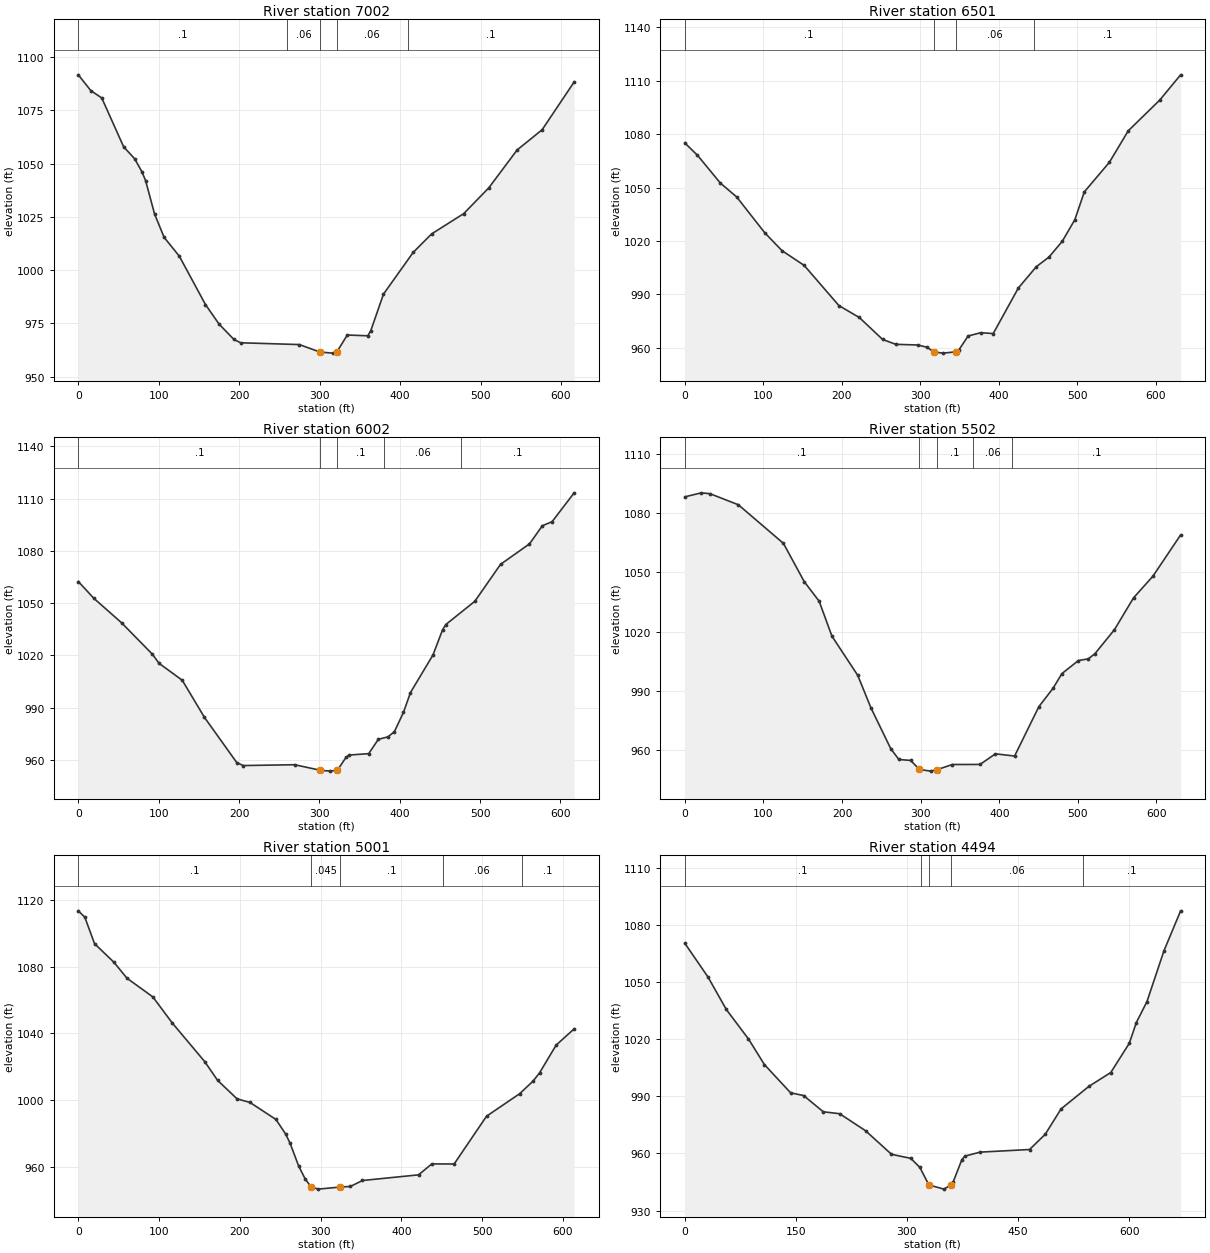
Type RM Length L Ch R = 1 ,7002    ,505.9,501.1,489.7
BEGIN DESCRIPTION:
Structure 2 XS 1
END DESCRIPTION:
XS GIS Cut Line= 6
1678658.45587109436391.7472650861678742.64730376436436.897765338
1678818.50312318436482.849117011 1678876.9452635436529.910702676
1679076.25031109436700.7433662561679155.79345909436751.924038172
#Sta/Elev= 30
       0  1091.7    15.5 1084.29    29.1 1080.85    56.3 1057.93      70 1052.31
      79 1046.24    83.6 1042.08    94.8 1026.33   106.6 1015.44   125.5 1006.59
     158   983.9     175  974.67   193.3  967.54   201.7  965.94   274.7   965.1
   300.2  961.61   300.2   961.6   316.1  961.08   321.4  961.68   334.3  969.58
   359.8  969.22   363.5  971.61   379.3  988.78   416.2 1008.35   439.2 1017.05
     479 1026.55   510.2 1038.66   545.4 1056.43   576.5 1065.93   616.3 1088.36
#Mann= 5, -1 ,  0
       0     0.1       0  259.26    0.06       0   300.2   0.045       0
   321.4    0.06       0  409.26     0.1       0
Bank Sta=300.2,321.4
XS Rating Curve= 0 ,0
Exp/Cntr(USF)=0,0
Exp/Cntr=0.3,0.1

Type RM Length L Ch R = 1 ,6501    ,485.6,498.7,522.5
XS GIS Cut Line= 6
1678532.60605717436982.2382100821678629.32338342437010.248980835
1678721.56663726437024.6367473451678801.25512618437031.161012501
1678902.57775818437031.5914578441679158.82757376437031.591457844
#Sta/Elev= 30
       0 1075.07    16.1 1068.16    45.3 1052.53    66.1 1044.74   101.6 1024.77
   123.8 1014.59   152.1 1006.31   196.3  983.75   222.3  977.07     252  964.75
   268.8  962.01   296.9  961.64   308.9  960.33   316.9  957.74   328.9  957.07
   344.9  957.77   348.9  958.72   360.9  966.69   376.9  968.53   392.9  968.07
   424.9  993.63   447.9 1005.64   463.9 1010.98   480.9  1019.9   496.9 1032.02
   508.9 1047.58   540.9 1064.22   564.9 1081.88   604.9 1099.07   631.6 1113.29
#Mann= 4, -1 ,  0
       0     0.1       0   316.9   0.045       0   344.9    0.06       0
  445.33     0.1       0
Bank Sta=316.9,344.9
XS Rating Curve= 0 ,0
Exp/Cntr(USF)=0,0
Exp/Cntr=0.3,0.1

Type RM Length L Ch R = 1 ,6002    ,503.4,500.1,487.8
XS GIS Cut Line= 6
1678469.94345284437046.1206282531678503.99850284437138.013817176
1678513.98273484437225.1652176681678517.20549743437300.096170172
 1678524.7254955437474.9344031661678532.51452193437656.016718179
#Sta/Elev= 30
       0 1062.37    19.1 1052.83    53.8  1038.7    92.2 1020.62   100.5  1015.4
   129.3 1005.71   156.9  984.42   197.1  958.46   205.1  956.72   269.2   957.2
   301.2  954.01   313.2  953.52  322.45954.0833   333.2  961.49   337.2  962.76
   361.3  963.56   373.3  971.77   385.3   973.2   393.3  976.18   404.6  987.25
   413.3  998.63   441.3 1020.21   453.3 1034.69   457.3 1037.69   493.4 1051.04
   525.4 1072.25   561.4    1084   577.5 1094.44   589.5 1096.73     617 1113.31
#Mann= 5, -1 ,  0
       0     0.1       0   301.2   0.045       0  322.45     0.1       0
  380.72    0.06       0  475.72     0.1       0
Bank Sta=301.2,322.45
XS Rating Curve= 0 ,0
Exp/Cntr(USF)=0,0
Exp/Cntr=0.3,0.1

Type RM Length L Ch R = 1 ,5502    ,512.4,501.3,485.4
XS GIS Cut Line= 6
1677847.30395009437096.5188214181677907.81596817437168.124321252
 1678077.2503406437368.619327083  1678120.216462 437430.50371775
1678147.75019959437520.3585249191678170.78591467437622.960353836
#Sta/Elev= 30
       0 1088.34      21 1090.39    32.2 1089.93    68.1 1084.34   125.5 1064.74
   151.9 1045.35   170.9 1035.41   187.2 1017.65     220   997.8   236.7  981.38
   261.9  960.66   272.3  955.11   287.3  954.64   298.5  950.05   312.8  949.21
   321.3  950.01   340.4  952.57   375.6   952.6   395.1  957.99   419.5  956.86
   450.4  981.93   468.4  991.23   479.7  998.68   500.7 1005.32   513.2 1006.16
   521.6 1008.74   546.5 1020.95   570.8 1037.12   595.4 1048.07   630.7 1069.03
#Mann= 5, -1 ,  0
       0     0.1       0   298.5   0.045       0   321.3     0.1       0
  366.25    0.06       0  416.25     0.1       0
Bank Sta=298.5,321.3
XS Rating Curve= 0 ,0
Exp/Cntr(USF)=0,0
Exp/Cntr=0.3,0.1

Type RM Length L Ch R = 1 ,5001    ,476.6,507,515.4
XS GIS Cut Line= 6
1677444.08625259437683.8575417551677624.84606168 437697.17674084
 1677799.3729436437710.0379355851677874.17003809437715.549407512
1677961.43364309437721.9801689241678053.72512518437745.221920341
#Sta/Elev= 30
       0 1113.56       8 1109.76    20.1 1093.82    44.1 1082.68    60.2 1073.12
    92.3 1061.87   116.3 1046.23   156.5 1023.03   172.5 1011.75   196.6 1000.66
   212.6  998.51   244.7  988.29   256.7  979.54   262.2  974.02   272.8  960.34
   280.8  952.67  288.02947.9293   296.8  946.48     324  947.73   336.9  948.09
   351.8  951.66   421.2  955.05   437.7  961.63   465.3  961.56   505.4  990.25
   546.3 1003.73   562.8 1011.21     571 1016.23   591.6 1032.94   613.9  1042.7
#Mann= 5, -1 ,  0
       0     0.1       0  288.02   0.045       0     324     0.1       0
  451.25    0.06       0  548.75     0.1       0
Bank Sta=288.02,324
XS Rating Curve= 0 ,0
Exp/Cntr(USF)=0,0
Exp/Cntr=0.3,0.1

Type RM Length L Ch R = 1 ,4494    ,508.5,492.2,481.7
XS GIS Cut Line= 6
1677451.91924217437950.2749879211677645.11964317438032.844376594
  1677715.650342438086.0007663371677733.22839084438185.781406671
1677763.16271417438258.313741922   1677860.31147 438422.75271751
#Sta/Elev= 30
       0 1070.35    31.4 1052.57      56 1035.59      86 1020.08   107.5 1006.65
   142.8  991.85   160.5  990.37     187  981.86   209.1  980.85     244  971.94
   279.1  959.54   305.2  957.41   317.4  952.64   329.6  943.47   349.9  941.26
  359.35943.4788   362.1  944.78   374.2  956.81   378.3  958.59   398.6  960.68
   465.5  962.06   486.6  970.01   508.1  983.39   545.7  995.22   575.2 1002.48
   600.2 1017.82   609.7 1028.71     624 1039.66     647 1066.38   669.5 1087.36
#Mann= 5, -1 ,  0
       0     0.1       0  318.55    0.06       0   329.6   0.045       0
  359.35    0.06       0  538.34     0.1       0
Bank Sta=329.6,359.35
XS Rating Curve= 0 ,0
Exp/Cntr(USF)=0,0
Exp/Cntr=0.3,0.1

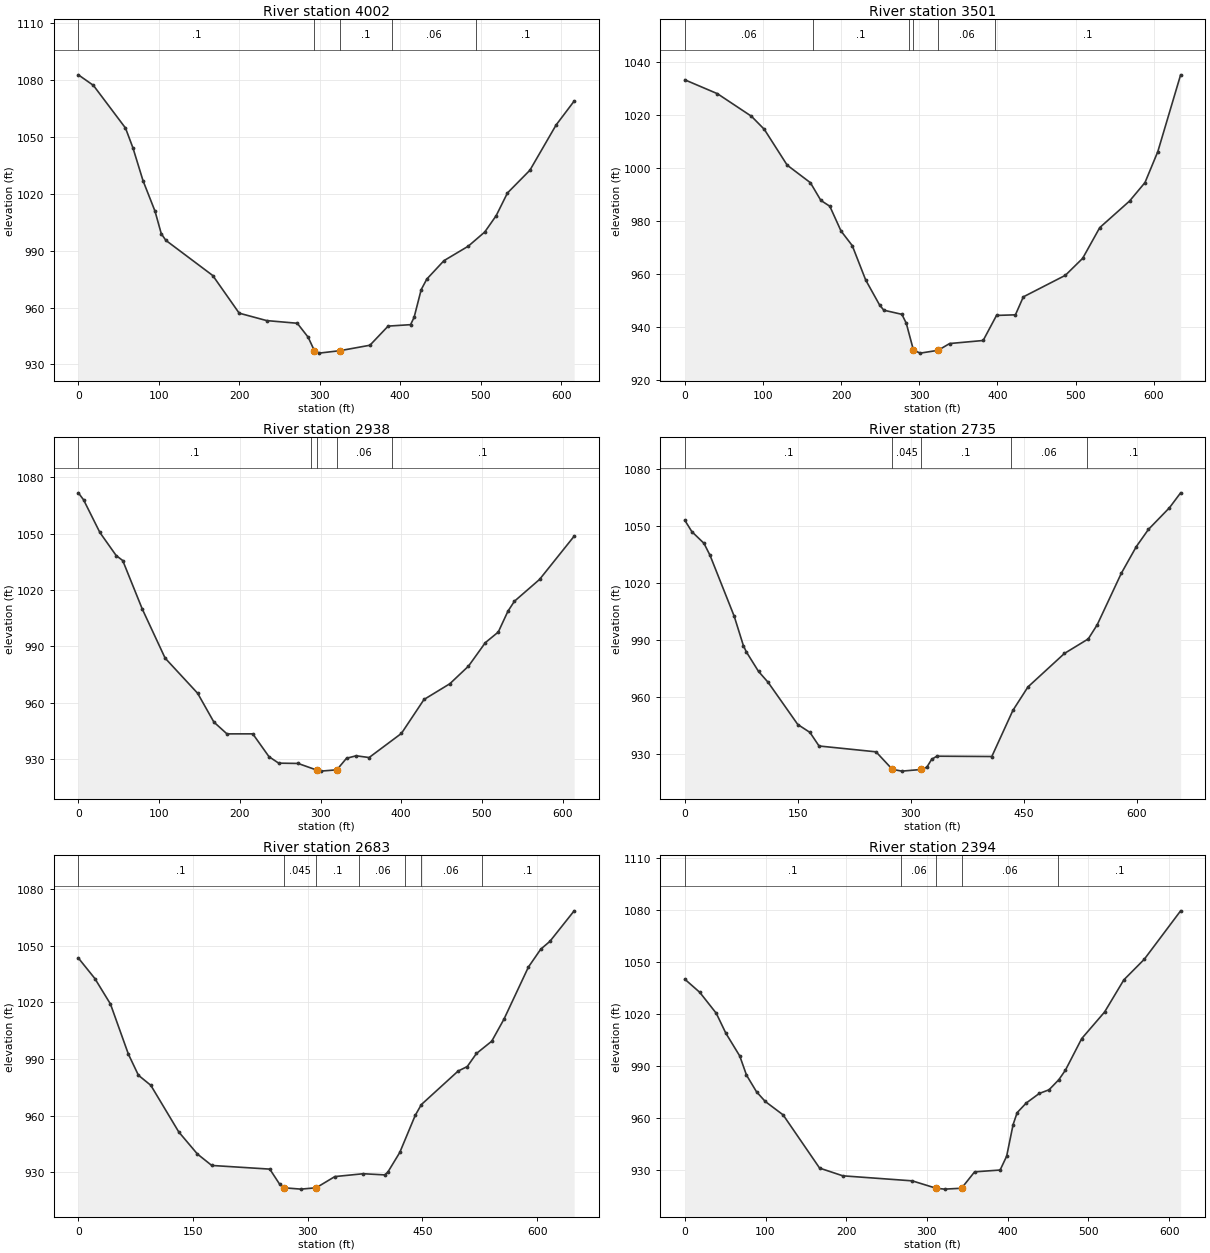
Type RM Length L Ch R = 1 ,4002    ,497.4,501,499.7
XS GIS Cut Line= 6
1677180.16125551438334.8808460091677246.13061176438405.585429013
1677318.61898383438455.4032427521677473.73022218438536.430639759
1677539.08442217438573.3052379191677695.40924075438665.508137509
#Sta/Elev= 30
       0 1082.63    18.7 1077.08    58.6 1054.59    67.9 1044.09    80.4 1026.84
    95.3 1010.77   103.1  998.87   108.8  995.39   167.1  976.85   199.9  957.03
     234  953.12   272.1  951.71   285.6  944.37   293.3  937.33   299.2  935.97
   325.3  937.27   362.4  940.13     385  950.21   412.9  950.97   417.3  954.84
   426.1  969.43   433.1  975.01   454.4   984.7   484.6  992.33   505.1   999.8
   519.3 1008.42   533.3 1020.37   561.2 1032.36   593.7 1056.16   616.2  1068.8
#Mann= 5, -1 ,  0
       0     0.1       0   293.3   0.045       0   325.3     0.1       0
  389.66    0.06       0   494.7     0.1       0
Bank Sta=293.3,325.3
XS Rating Curve= 0 ,0
Exp/Cntr(USF)=0,0
Exp/Cntr=0.3,0.1

Type RM Length L Ch R = 1 ,3501    ,568.1,562.4,551.6
XS GIS Cut Line= 6
1676773.47145209438572.2055025851676981.99662559438721.631384835
1677067.18772817438774.1640881751677128.57376026438820.850674585
1677198.06837192438884.6120299991677271.46783142438961.667650178
#Sta/Elev= 30
       0 1033.29    41.8 1028.04    85.3 1019.52   101.7  1014.6     131 1001.07
   160.7  994.45   174.1  987.76   185.6  985.54   199.9  976.21   214.3  970.68
   231.5  957.69   249.3  948.25   254.7   946.3   277.8  944.74   283.4  941.39
   292.6  931.23   301.3  930.09   324.1  931.15   338.9  933.71   381.8  934.86
   398.9  944.33   423.1  944.55   433.2  951.33     487  959.47   509.1  965.87
     531  977.48   569.1   987.5   588.9  994.49   605.3 1006.17   634.5 1035.17
#Mann= 6, -1 ,  0
       0    0.06       0  163.76     0.1       0  286.54    0.06       0
   292.6   0.045       0   324.1    0.06       0  396.62     0.1       0
Bank Sta=292.6,324.1
XS Rating Curve= 0 ,0
Exp/Cntr(USF)=0,0
Exp/Cntr=0.3,0.1

Type RM Length L Ch R = 1 ,2938    ,192.2,203.6,217.6
BEGIN DESCRIPTION:
Structure 1 XS 4
END DESCRIPTION:
XS GIS Cut Line= 5
1676617.64532018439314.0402236511676711.39546075439301.161968567
1676798.89528576439290.0540511541676873.89546384439285.456291311
1677230.14540751439285.456291311
#Sta/Elev= 30
       0 1071.73     6.5    1068    26.7 1050.61    46.9 1038.32      55 1035.67
    79.2 1009.86   107.5  983.71   147.8  964.99   167.9  949.66   184.1  943.37
   216.1  943.38   236.2  931.21   248.2  927.78   272.2  927.62   295.3   924.1
   300.2  923.53   320.2  924.22   332.2  930.37   344.2   931.7   360.2  930.77
   400.2   943.6   428.2  961.68   460.2  970.06   483.3  979.44   504.2  991.95
   520.2   997.6   532.2 1008.72   540.2 1013.99   571.3  1025.6   614.2 1048.65
#Mann= 5, -1 ,  0
       0     0.1       0  287.97    0.06       0   295.3   0.045       0
   320.2    0.06       0  387.97     0.1       0
Bank Sta=295.3,320.2
XS Rating Curve= 0 ,0
Exp/Cntr(USF)=0,0
Exp/Cntr=0.3,0.1

Type RM Length L Ch R = 1 ,2735    ,54.7,52.1,53.6
BEGIN DESCRIPTION:
Structure 1 XS 3
END DESCRIPTION:
XS GIS Cut Line= 6
1676630.75652681439393.9209846111676840.75161135439415.432676198
1676855.09273908439450.2611292441676867.38513427439468.699722034
1676942.16387169439539.3809943921677226.93769366439534.259163061
#Sta/Elev= 30
       0 1053.08     9.4 1047.08    25.5 1040.94    33.5 1034.66    65.7 1002.56
    77.8  987.23    81.8  983.88    97.9  973.66   110.6  967.95   150.1  945.74
   166.2  941.61   178.3  934.46     254  931.39  275.68922.1829   288.4  921.25
   313.8  922.11   321.5  923.33   327.9  927.44   334.7   929.1   407.8  928.93
   435.8  953.16   455.8  965.49   504.3   983.1   535.9  990.72   547.8  998.15
   579.8  1025.2   599.8 1039.27   615.8 1048.25   643.8 1059.67   658.6 1067.49
#Mann= 5, -1 ,  0
       0     0.1       0  275.68   0.045       0   313.8     0.1       0
  433.82    0.06       0  533.82     0.1       0
Bank Sta=275.68,313.8
XS Rating Curve= 0 ,0
Exp/Cntr(USF)=0,0
Exp/Cntr=0.3,0.1

Type RM Length L Ch R = 1 ,2683    ,297.2,289,267.4
BEGIN DESCRIPTION:
Structure 1 XS 2
END DESCRIPTION:
XS GIS Cut Line= 6
1676634.85399188439417.4814087311676801.82569324439448.212396712
1676849.97090775439516.8449365381676909.38415118439560.892685979
1676943.18823796439582.4043775661677223.86459486439571.136348639
#Sta/Elev= 30
       0 1043.51    21.6 1032.63      42 1019.12    65.5  992.51    78.6  981.35
    94.8  976.02   131.4  951.27   155.8  939.58   174.5  933.54   250.4   931.6
   263.5  923.48  268.41921.7197   291.1  920.99   311.1  921.71   335.5  927.64
   372.6  929.15   400.6  928.54   404.6  929.88   420.4  940.41   440.6  960.06
   448.6  965.79   496.7  983.57   508.7  985.97   520.7  992.89   540.7   999.4
   556.7 1011.09   588.7 1038.73   604.8 1048.18   616.8 1052.34   648.5 1068.51
#Mann= 7, -1 ,  0
       0     0.1       0  268.41   0.045       0   311.1     0.1       0
  367.57    0.06       0  427.64     0.1       0  447.64    0.06       0
  527.64     0.1       0
Bank Sta=268.41,311.1
XS Rating Curve= 0 ,0
Exp/Cntr(USF)=0,0
Exp/Cntr=0.3,0.1

Type RM Length L Ch R = 1 ,2394    ,391,392.8,394.5
BEGIN DESCRIPTION:
Structure 1 XS 1
END DESCRIPTION:
XS GIS Cut Line= 6
1676646.51967088439877.7315287411676737.59363572439852.227314663
1676823.33493405 439832.011147751676896.93682098439816.497071159
 1677156.4750158439777.1759555761677248.77371571439760.535896999
#Sta/Elev= 30
       0 1040.18    18.5 1032.63      39 1020.54    50.9 1009.03    68.1  995.93
    76.4  984.96    88.9  975.29    99.7  969.74   121.8  962.03     167  931.38
   195.7  926.94   281.7  924.04   311.4919.7704   321.8  919.27   342.8  919.78
     359  929.22   390.6  930.27   398.7  938.24   406.7  956.47   411.7  963.31
   422.9  968.84   439.1  974.37   451.2  976.48   463.4  982.33   471.5  987.79
   491.7 1005.99     520 1021.27   543.9 1039.81   569.1 1051.61   614.2 1079.55
#Mann= 5, -1 ,  0
       0     0.1       0  267.89    0.06       0   311.4   0.045       0
   342.8    0.06       0  462.89     0.1       0
Bank Sta=311.4,342.8
XS Rating Curve= 0 ,0
Exp/Cntr(USF)=0,0
Exp/Cntr=0.3,0.1

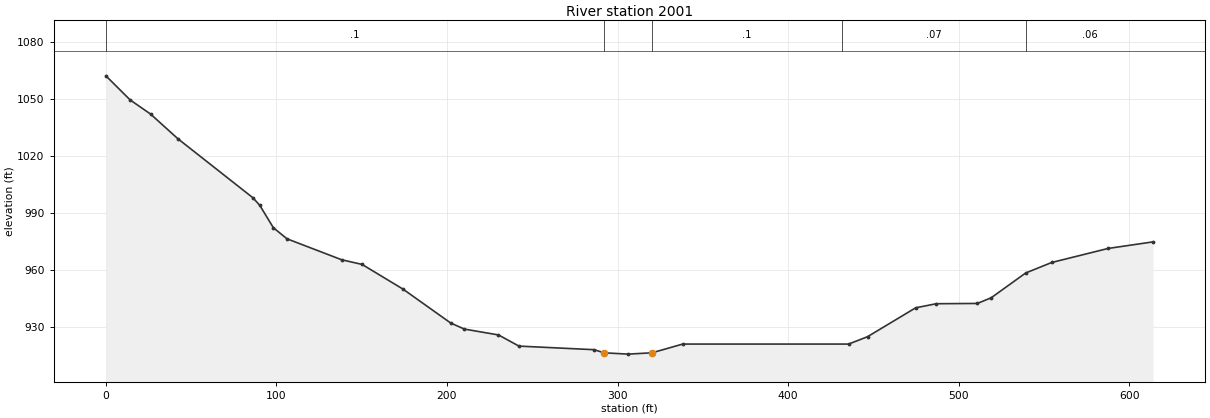
Type RM Length L Ch R = 1 ,2001    ,494.1,497.3,504.5
XS GIS Cut Line= 5
1676765.88419692440174.4713269171677122.13446867440174.471326917
1677197.13431868440181.000513345 1677284.6295505440191.210794762
1677378.18546575440203.426321507
#Sta/Elev= 30
       0 1062.41    14.2 1049.72    26.2 1042.25    42.2 1029.26    86.2  998.15
    90.2  994.19    98.2  982.35   106.2  976.52   138.2  965.49   150.2  963.03
   174.2  950.02   202.2  932.13   210.2  928.95   230.2  925.86   242.2  919.98
   286.2  918.09   292.2  916.44   306.2  915.75   320.2  916.45   338.2  921.05
   435.5  921.05   446.6  924.94   474.8  940.16   486.9  942.31     511  942.46
   519.1  945.46   539.3   958.5   554.6  964.05   587.7  971.45     614  974.91
#Mann= 5, -1 ,  0
       0     0.1       0   292.2   0.045       0   320.2     0.1       0
  431.53    0.07       0  539.62    0.06       0
Bank Sta=292.2,320.2
XS Rating Curve= 0 ,0
Exp/Cntr(USF)=0,0
Exp/Cntr=0.3,0.1