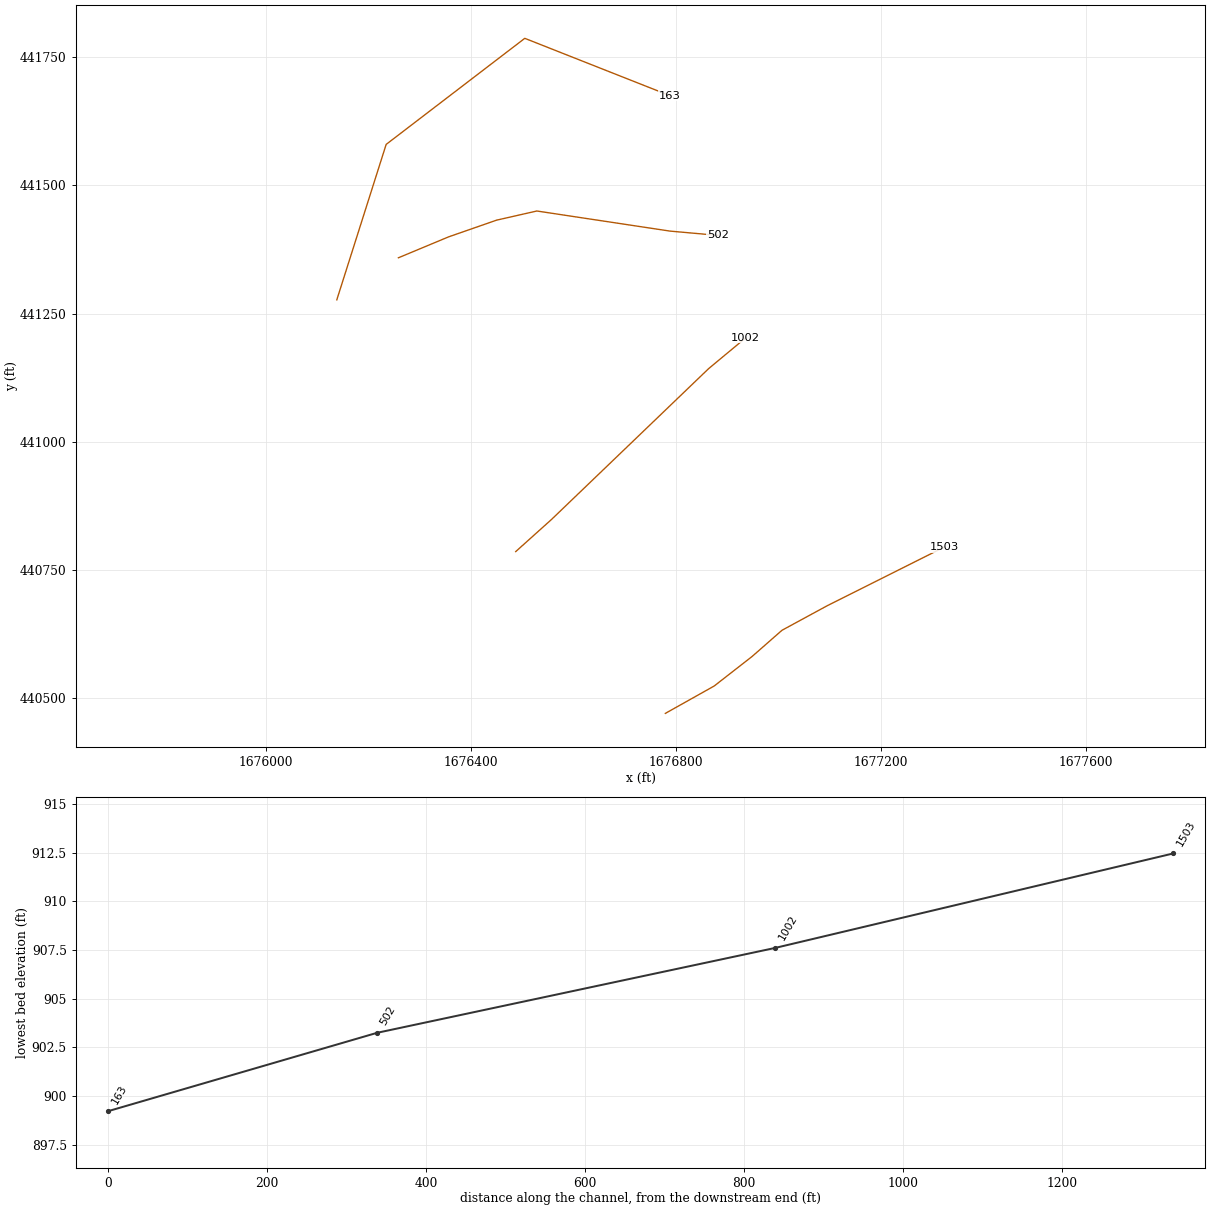
HEC-RAS study SUGARRN.prj: SUGARRN

--- SUGARRN.g01 (geometry) --- (continued)

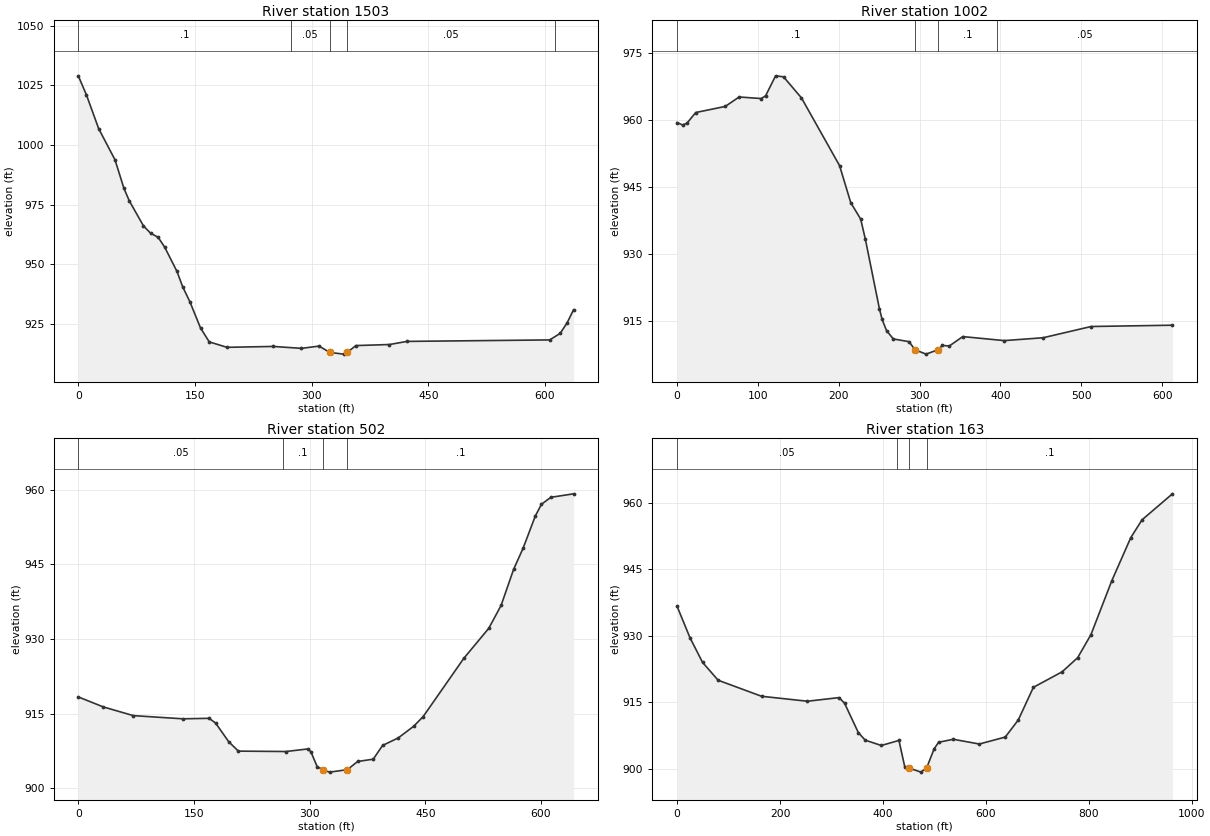
Type RM Length L Ch R = 1 ,1503    ,499.4,501.3,504.3
XS GIS Cut Line= 6
1676778.97012876440469.9950140861676874.23043692440523.369251177
1676948.24374034440581.0390833321677006.55825625440632.140359089
1677094.47474709440679.8594237571677323.57763533440794.646267667
#Sta/Elev= 30
       0    1029    10.5 1020.98    26.2 1006.87    47.2  993.83    58.5  982.05
    65.5  976.68    83.8  966.16      93  963.09   102.6   961.4   111.1  957.25
   126.8  947.14   134.2  940.67   143.6   934.3   157.2  923.37   168.4  917.59
   191.2  915.32   250.8  915.69   286.9  914.88   309.6  915.84   323.3   913.2
   323.3  913.19     341  912.47     346  913.23   356.9  916.05     400  916.49
   422.7   917.8   606.1  918.42   619.5  921.14   628.5  925.56   636.8  931.07
#Mann= 5, -1 ,  0
       0     0.1       0  273.02    0.05       0   323.3   0.045       0
     346    0.05       0  613.09     0.1       0
Bank Sta=323.3,346
XS Rating Curve= 0 ,0
Exp/Cntr(USF)=0,0
Exp/Cntr=0.3,0.1

Type RM Length L Ch R = 1 ,1002    ,510.5,500.5,483.3
XS GIS Cut Line= 6
1676487.02648692440785.5698422491676556.84032367440848.219651341
1676746.20411818441030.0096420941676800.30801259441081.949826926
1676863.42960551441142.5461624261676935.74606192441202.589349419
#Sta/Elev= 30
       0  959.48     6.8  958.96    12.2  959.37      23  961.75    59.5  963.11
    76.7  965.23   103.9  964.88   109.4  965.48   121.8  969.97   131.6  969.75
   153.8  965.03     201  949.83   214.8  941.55   227.1  937.86   232.9  933.34
   250.2  917.82   253.6  915.38   259.1  912.87   267.5  911.01   286.9   910.4
   294.4  908.58     308  907.61  322.36908.5681   328.3  909.55   336.8  909.44
   353.4  911.54   404.7  910.64   452.8  911.28   512.2   913.8   612.8  914.09
#Mann= 4, -1 ,  0
       0     0.1       0   294.4   0.045       0  322.36     0.1       0
   396.3    0.05       0
Bank Sta=294.4,322.36
XS Rating Curve= 0 ,0
Exp/Cntr(USF)=0,0
Exp/Cntr=0.3,0.1

Type RM Length L Ch R = 1 ,502     ,325.4,338.6,349.2
XS GIS Cut Line= 6
 1676258.2165771441358.7373310921676355.99623717441399.505622253
1676449.62498692441432.1230110821676528.25343859 441450.01044251
1676787.82772259441410.8369644281676881.45811276441402.439343423
#Sta/Elev= 30
       0  918.36    32.4  916.35    71.4   914.6   135.7  913.96   169.7  914.06
   178.1   913.1     195  909.37   207.6  907.47   269.2  907.39   297.7  907.91
   301.7  907.32   309.8  904.34   317.9   903.7   325.9  903.25  348.93 903.743
   362.3  905.39   382.5  905.85   394.6  908.61   414.9  910.12     435  912.47
   447.3  914.42   499.9   926.1   532.3  932.14   548.3  936.74   564.6  944.01
   576.9  948.25   592.7  954.71   600.7  957.07   612.8  958.46   642.3  959.16
#Mann= 4, -1 ,  0
       0    0.05       0  265.09     0.1       0   317.9   0.045       0
  348.93     0.1       0
Bank Sta=317.9,348.93
XS Rating Curve= 0 ,0
Exp/Cntr(USF)=0,0
Exp/Cntr=0.3,0.1

Type RM Length L Ch R = 1 ,163     ,,,
XS GIS Cut Line= 4
1676138.03635284441276.7061816281676234.32678185441579.918596382
1676504.75947609441786.8405821261676787.48456552441675.184659125
#Sta/Elev= 30
       0  936.58      25  929.52    49.3  923.99    79.6  919.95     164  916.33
   253.2  915.21   314.6  916.03   325.4  914.76   352.1  908.14   365.5  906.43
   396.9  905.23   431.1  906.37   442.5  900.35   451.1  900.12   473.9  899.22
  485.02900.2048   499.6  904.51   508.2  905.95   536.7  906.63   587.3  905.56
   637.7  907.13     663  910.98   692.4  918.35   748.3  921.85   778.4  925.03
   804.2  930.22   844.9  942.42   881.6  952.09   903.5  956.12   962.6  961.99
#Mann= 4, -1 ,  0
       0    0.05       0  428.13     0.1       0   451.1   0.045       0
  485.02     0.1       0
Bank Sta=451.1,485.02
XS Rating Curve= 0 ,0
Exp/Cntr(USF)=0,0
Exp/Cntr=0.3,0.1
LCMann Table=0

Chan Stop Cuts=-1
Use User Specified Reach Order=0
Composite Channel Slope=5